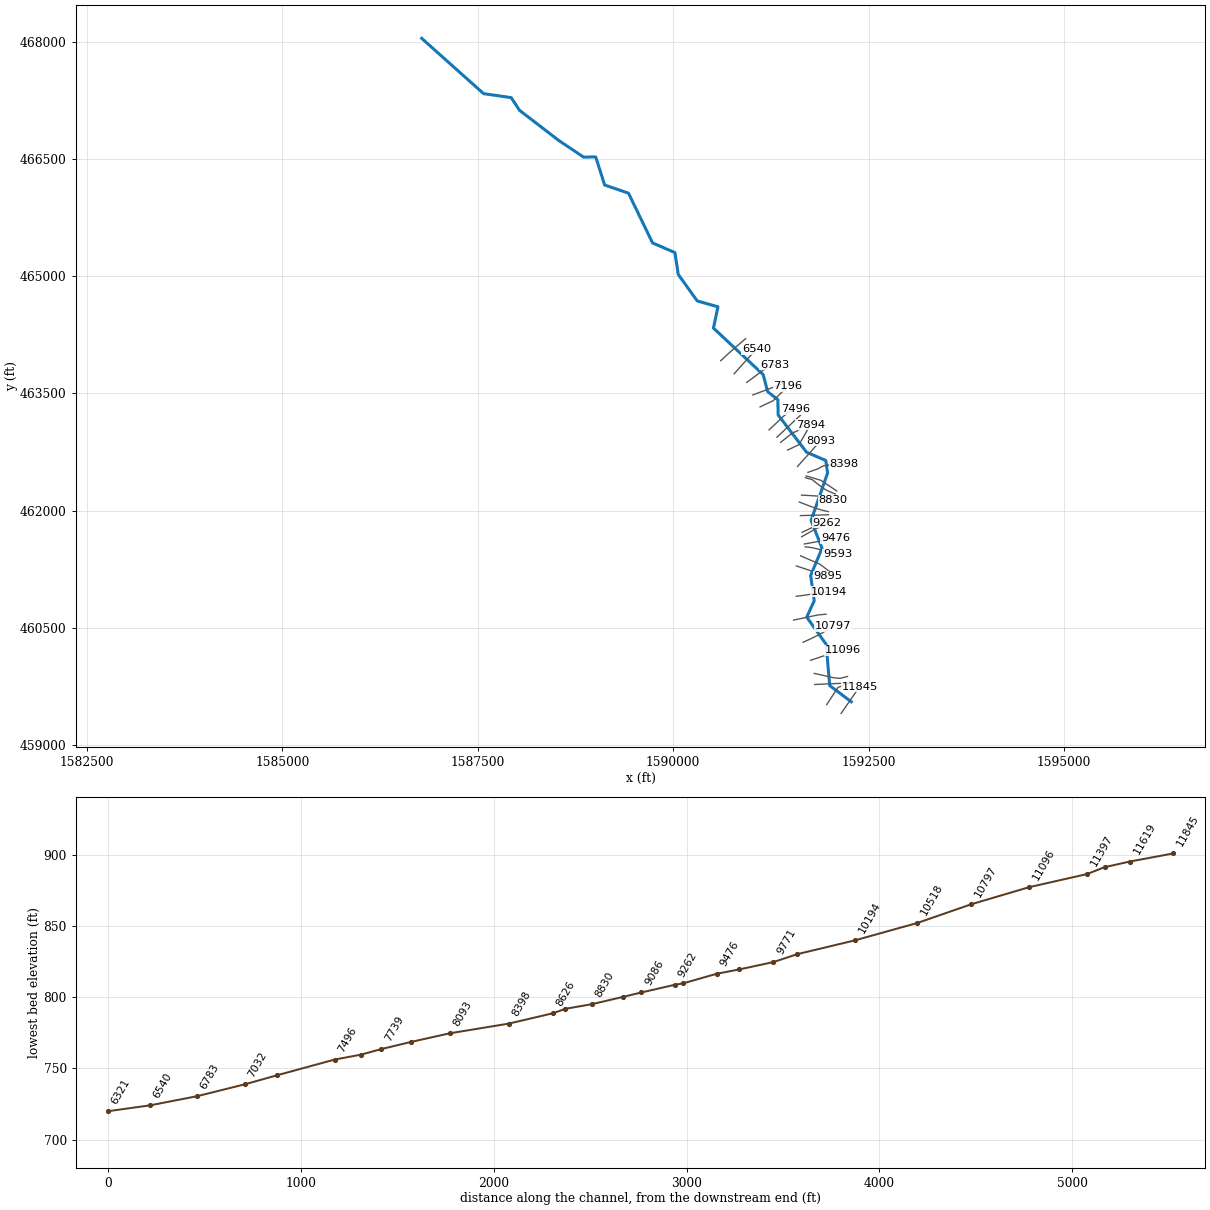
--- SimsRn.prj (project) ---

Proj Title=SimsRn
Current Plan=p01
Default Exp/Contr=0,0
English Units
Geom File=g01
Flow File=f01
Plan File=p01
BEGIN DESCRIPTION:
---------- MODELED AS PART OF WVEM CTP PROGRAM, 2025----------
Stream Name: Sims Run
Flood Zone: AFH
Marshall County, WV
HEC-RAS Version: RAS 6.6
Vertical Datum: NAVD88
Projection: NAD 1983 StatePlane West Virginia N FIPS 4701 (US Feet)
Terrain: 1-meter West Virginia FEMA R3 South Central (collected 2018-2019)
Land Use: 2024 NLCD
Hydrologic Method:
Duda et al., "Estimation of magnitude and frequency of floods for rural, unregulated streams in and near Virginia and West Virginia." September 8, 2025.
Additional Model Notes:
None
END DESCRIPTION:
DSS Export Rating Curves= 0
DSS Export Rating Curve Sorted= 0
DSS Export Volume Flow Curves= 0
DXF OffsetX= 0
DXF OffsetY= 0
DXF ScaleX= 0
DXF ScaleY= 0

--- SimsRn.p01 (plan) ---

Plan Title=Floodplain
Program Version=6.60
Short Identifier=Floodplain
Geom File=g01
Flow File=f01
Subcritical Flow
K Sum by GR= 0
Std Step Tol= 0.01
Critical Tol= 0.01
Num of Std Step Trials= 20
Max Error Tol= 0.3
Flow Tol Ratio= 0.001
Split Flow NTrial= 30
Split Flow Tol= 0.02
Split Flow Ratio= 0.02
Log Output Level= 0
Friction Slope Method= 1
Unsteady Friction Slope Method= 2
Unsteady Bridges Friction Slope Method= 1
Parabolic Critical Depth
Global Vel Dist= 0 , 0 , 0
Global Log Level= 0
CheckData=True
Encroach Param=-1 ,0,0, 0
Flow Ratio Tolerance=0.1
Flow Ratio Min Ratio=0.5
Flow Ratio Max Ratio=4
Flow Ratio Max Iterations= 10
Computation Interval=1MIN
Output Interval=1HOUR
Instantaneous Interval=1HOUR
Mapping Interval=1HOUR
Computation Time Step Use Courant=        0
Computation Time Step Use Time Series=    0
Computation Time Step Count To Double=0
Computation Time Step Max Doubling=0
Computation Time Step Max Halving=0
Computation Time Step Residence Courant=0
Run HTab= 0
Run UNet= 0
Run Sediment= 0
Run PostProcess= 0
Run WQNet= 0
Run RASMapper=-1
UNET Theta= 1
UNET Theta Warmup= 1
UNET ZTol= 0.02
UNET ZSATol= 0.02
UNET MxIter= 20
UNET Max Iter WO Improvement= 0
UNET MaxInSteps= 0
UNET DtIC= 0
UNET DtMin= 0
UNET MaxCRTS= 20
UNET WFStab= 2
UNET SFStab= 1
UNET WFX= 1
UNET SFX= 1
UNET Gravity=32.17405
UNET 1D Methodology=Finite Difference
UNET DSS MLevel= 4
UNET Pardiso=0
UNET DZMax Abort= 100
UNET Use Existing IB Tables=-1
UNET Froude Reduction=False
UNET Froude Limit= 0.8
UNET Froude Power= 4
UNET D1 Cores= 0
UNET WindReference=Eulerian
UNET WindDragFormulation=Hsu (1988)
UNET D2 Coriolis=0
UNET D2 Cores= 0
UNET D2 Theta= 1
UNET D2 Theta Warmup= 1
UNET D2 Z Tol= 0.01
UNET D2 Volume Tol= 0.01
UNET D2 Max Iterations= 20
UNET D2 Advanced Convergence=0
UNET D2 WS Max Tol=0.15
UNET D2 WS RMS Tol=0.002
UNET D2 WS Stall Tol=1
UNET D2 Equation= 0
UNET D2 RampUpFraction=0.1
UNET D2 TimeSlices= 1
UNET D2 Turbulence Formulation=None
UNET D2 Eddy Viscosity=0.3
UNET D2 Transverse Eddy Viscosity=0.1
UNET D2 Smagorinsky Mixing=0.05
UNET D2 BCVolumeCheck=0
UNET D2 Cores=0
UNET D2 SolverType=PARDISO (Direct)
UNET D2 Minimum Iterations= 3
UNET D2 Maximum Iterations= 30
UNET D2 Restart Number= 10
UNET D2 Relaxation Coeff=1.3
UNET D2 SOR Precondition Iterations= 10
UNET D2 ILUT Maximum Fill= 8
UNET D2 ILUT Tolerance=1E-08
UNET D2 Convergence Tolerance=0.00001
PS Theta= 1
PS WS Tol= 0.01
PS Volume Tol= 0.01
PS Max Iterations= 20
PS Equation= 0
PS Advance Time Step=-1
PS Target Courant=0.9
PS Time Slices= 1
PS Iterate With 2D=0
PS Project Initial WSE from DS=-1
PS Ramp Up Initial WSE from US=-1
PS Cores=0
UNET D1D2 MaxIter= 0
UNET D1D2 ZTol=0.01
UNET D1D2 QTol=0.1
UNET D1D2 MinQTol=1
Write IC File= 0
Write IC File at Fixed DateTime=0
Write IC File at Sim End=0
Echo Input=False
Echo Parameters=False
Echo Output=False
Write Detailed= 0
HDF Write Warmup=0
HDF Write Time Slices=0
HDF Flush=0
HDF Compression= 1
HDF Chunk Size= 1
HDF Spatial Parts= 1
HDF Use Max Rows=0
HDF Fixed Rows= 1
Calibration Method= 0
Calibration Iterations= 20
Calibration Max Change=0.05
Calibration Tolerance=0.2
Calibration Maximum=1.5
Calibration Minimum=0.5
Calibration Optimization Method= 1
WQ AD Non Conservative
WQ ULTIMATE=-1
WQ Max Comp Step=1HOUR
WQ Output Interval=15MIN
WQ Output Selected Increments= 0
WQ Create Restart=0
WQ Fixed Restart=0
WQ System Summary=0
WQ Write To DSS=0
Sorting and Armoring Iterations= 10
XS Update Threshold= 0.02
Bed Roughness Predictor= 0
Processes Affected by Predictor=Sediment Only
Hydraulics Update Threshold= 0.02
Energy Slope Method= 1
Volume Change Method= 1
Sediment Retention Method= 0
Sediment TS Multiplier= 1
Warm Up Method= 0
XS Weighting Method= 0
Number of US Weighted Cross Sections= 1
Number of DS Weighted Cross Sections= 1
Upstream XS Weight=0
Main XS Weight=1
Downstream XS Weight=0
Number of DS XS's Weighted with US Boundary= 1
Upstream Boundary Weight= 1
Weight of XSs Associated with US Boundary= 0
Number of US XS's Weighted with DS Boundary= 1
Downstream Boundary Weight= 0.5
Weight of XSs Associated with DS Boundary= 0.5
Percentile Method= 0
Sediment Output Level= 3
Mass or Volume Output= 0
Output Increment Type= 1
Profile and TS Output Increment= 1
Transport Output Increment 1
XS Output Flag= 0
XS Output Increment= 10
Read HDF5 Sediment Hotstart= 0
Sediment Hotstart Type= 0
Write Gradation File= 0
Read Gradation Hotstart= 0
Write HDF5 File= 1
Write Binary Output= 1
Write DSS Sediment File= 0
DSS Sediment Output Type= 1
SV Curve= 0
Specific Gage Flag= 0
Subcell Erosion Methods= 0
Subcell Deposition Methods= 0
Advection Scheme= 1
Matrix Solver= 0
Implicit Weighting Factor= 1
Maximum Outer Loop Convergence Iterations= 5
Convergence Maximum Absolute= 0.001
Convergence RMSE= 0.0001
Grain Fractions Max Abs Error= 0.001
Max Subgrid Regions= 1
Max Subgrid Length Scale= 3.402823E+38
Initial Layer Thickness= 3
Min Layer Thickness= 0.1
Max Layer Thickness= 6
Number of Layers= 5

--- SimsRn.f01 (steady flow) ---

Flow Title=Flow
Program Version=6.60
Number of Profiles= 1
Profile Names=P100yr
River Rch & RM=SimsRn,Main,11845
     727
River Rch & RM=SimsRn,Main,10797
     806
River Rch & RM=SimsRn,Main,8093
     946
River Rch & RM=SimsRn,Main,6540
    1010
River Rch & RM=SimsRn,Main,4800
    1150
Boundary for River Rch & Prof#=SimsRn,Main            , 1
Up Type= 0
Dn Type= 3
Dn Slope=0.01
DSS Import GetInterval= 0
DSS Import GetPeak= 0
DSS Import FillOption= 0

--- SimsRn.g01 (geometry) ---

Geom Title=Geometry
Program Version=6.60

River Reach=SimsRn          ,Main
Reach XY= 30
     1592279.297      459550.456     1592003.462      459757.864
     1591957.156      460286.837 1591709.0942065 460635.02424653
1591804.73909164460843.6538460831591759.25566497 461166.85372501
     1591905.002       461516.52     1591765.052      461873.825
     1591976.447      462481.226     1591953.282      462640.849
     1591707.462      462745.373     1591343.656      463223.353
     1591339.631      463418.8411591209.06772629463522.306660558
     1591152.077      463740.035     1590515.416      464336.059
     1590572.502      464608.914     1590308.062      464683.877
     1590064.528      465024.001     1590022.923      465302.662
     1589736.204      465426.246     1589428.021      466064.256
      1589123.02      466168.384      1589009.09      466527.666
     1588852.894      466526.545     1588537.025      466737.913
     1588033.305      467125.517     1587927.789      467286.868
     1587574.275      467338.389     1586781.617      468046.818

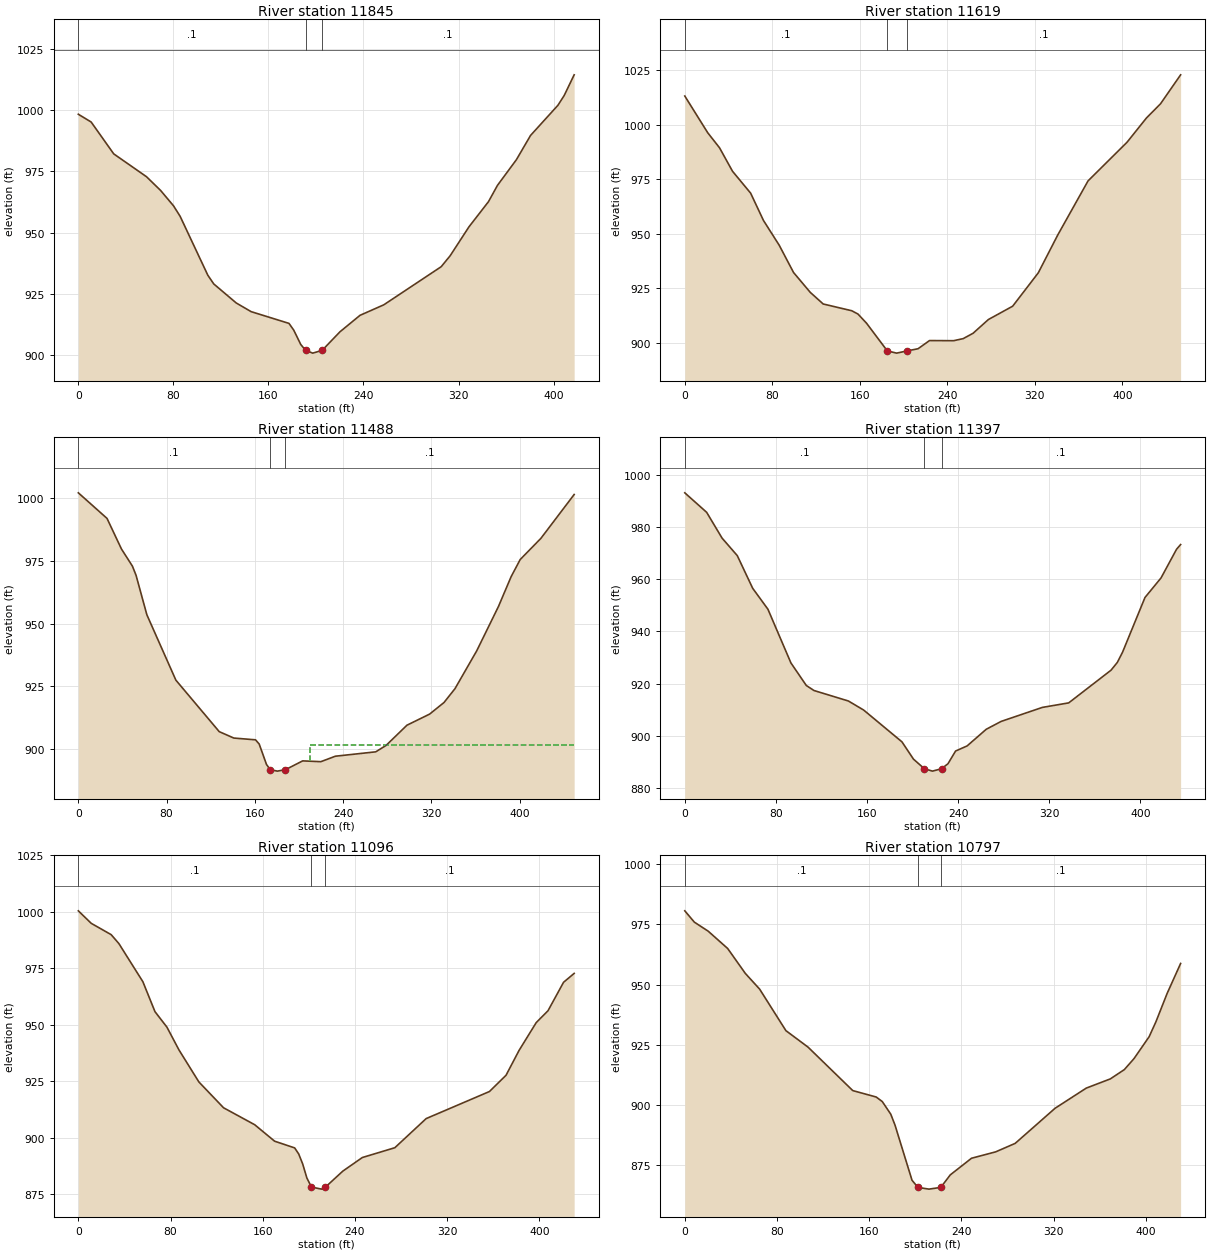
Type RM Length L Ch R = 1 ,11845   ,225.4,225.6,225.5
XS GIS Cut Line= 2
1592149.33349867459402.1096067721592386.34758717459745.579203965
#Sta/Elev= 30
       0  998.31    10.8  995.13    29.8  982.14    57.4  972.81    69.2  967.24
    80.1  960.96    85.7  956.65     109  932.62     114  929.07   132.9  921.31
   145.4  917.78   177.3  912.98   181.3  910.23   187.2  904.38  191.31901.9816
   197.3  900.85   205.2  901.98   220.2  909.55   237.1  916.28   257.1  920.56
   305.4  936.11   312.9  940.55   328.8  952.39   345.2  962.64   352.7  969.25
   368.7  979.77   380.6  989.66   403.6 1001.94   408.9 1005.94   417.3 1014.39
#Mann= 3 ,-1,0
       0      .1       0  191.31    .045       0   205.2      .1       0
Bank Sta=191.31,205.2
XS Rating Curve= 0 ,0
Exp/Cntr(USF)=0,0
Exp/Cntr=0.3,0.1

Type RM Length L Ch R = 1 ,11619   ,141.9,131.5,127.7
XS GIS Cut Line= 3
1591964.93439886459514.1546631111592109.37844422459734.347359117
1592287.19035492 459801.01866377
#Sta/Elev= 30
       0 1013.08    20.9  996.28    31.8   989.3    43.6  978.58    60.2  968.52
    71.9  956.01    86.3  944.65    99.4  932.14   114.7  923.02   126.5   917.7
   152.6   914.6   158.3  913.08   166.1  908.89  185.14896.1757   193.6  895.16
  203.15896.1753   213.2  897.18   223.7  900.92   245.7  900.86   254.5  901.82
   263.5  904.27   277.5  910.57   299.7  916.69   323.1  931.99   340.8  949.25
   368.6  974.16   404.2  991.87     422 1003.03   434.8  1009.5   453.2  1022.8
#Mann= 3 ,-1,0
       0      .1       0  185.14    .045       0  203.15      .1       0
Bank Sta=185.14,203.15
XS Rating Curve= 0 ,0
Exp/Cntr(USF)=0,0
Exp/Cntr=0.3,0.1

Type RM Length L Ch R = 1 ,11488   ,94.4,90.7,91.1
XS GIS Cut Line= 3
1591811.23412392459772.1121409191592217.14608952459789.728573422
1592257.51708067459804.408933842
#Sta/Elev= 30
       0 1002.25      26  992.04    39.1  979.82      49  973.01    52.3  969.35
    62.1  953.59    88.4  927.49   127.7  906.94   140.9  904.39   160.6  903.68
   163.9  901.99   170.5  893.87   173.8   891.8   180.3  891.19   187.7  891.77
   203.3  895.28   219.8  894.96   232.9  897.14   269.5  898.89   278.9  901.46
   297.8  909.52   318.3  913.94   331.4  918.59   341.3  924.09     361  939.19
   380.7  956.88   392.2   968.8   400.4  975.63   419.2   984.1   449.3 1001.58
#Mann= 3 ,-1,0
       0      .1       0   173.8    .045       0   187.7      .1       0
#XS Ineff= 2 , 0
                          209.75          901.51
Permanent Ineff=
       F       F
Bank Sta=173.8,187.7
XS Rating Curve= 0 ,0
Exp/Cntr(USF)=0,0
Exp/Cntr=0.3,0.1

Type RM Length L Ch R = 1 ,11397   ,298.5,300.9,306.7
XS GIS Cut Line= 6
1591805.32938084459914.272070333  1591890.688134 459895.03293559
1591963.85301392459878.5434672531592061.40596843459856.556962669
1592136.89859959   459850.8260031592231.19401467459874.506073758
#Sta/Elev= 30
       0  993.22    19.2  985.73    32.7  975.85    46.1   969.1    59.6  956.58
      73  948.53    93.2   927.9   106.7  919.25   113.4  917.32   143.7  913.28
   157.1   909.8   190.7   897.6   200.8  890.97  210.38 887.282   217.5  886.36
  225.46887.2819   231.1  889.19   237.8  894.08   247.9  896.03   264.7  902.43
   277.8  905.45     314  910.83   337.1  912.56   374.3  925.12   379.8  928.09
   384.4  932.02   404.1  953.03   418.2  960.54   431.8  971.53   435.4  973.36
#Mann= 3 ,-1,0
       0      .1       0  210.38    .045       0  225.46      .1       0
Bank Sta=210.38,225.46
XS Rating Curve= 0 ,0
Exp/Cntr(USF)=0,0
Exp/Cntr=0.3,0.1

Type RM Length L Ch R = 1 ,11096   ,296.2,299.3,299.4
XS GIS Cut Line= 6
1591757.68544726460081.7369585041591840.69512376460109.406522587
1591911.84655626460133.1230105911592006.13409734460166.489085585
1592079.75140418460188.9732925891592167.60030983460211.531646416
#Sta/Elev= 30
       0 1000.43    11.2  994.89    28.5  989.87    35.2  985.91      56  969.03
    66.5  955.76    76.9  948.88    87.3  938.82   104.6  924.62     126  913.18
     153  905.68   170.3  898.38   187.7   895.4   191.2  892.73   194.7  888.24
   198.3  882.05  202.28 878.045   211.1  877.14  214.41878.0453   229.5  885.12
   246.4  891.14   274.6  895.48   301.8  908.39   356.7  920.38   371.1  927.58
   382.4  938.59   397.3  950.92   407.5  956.16     421  968.77   430.2  972.71
#Mann= 3 ,-1,0
       0      .1       0  202.28    .045       0  214.41      .1       0
Bank Sta=202.28,214.41
XS Rating Curve= 0 ,0
Exp/Cntr(USF)=0,0
Exp/Cntr=0.3,0.1

Type RM Length L Ch R = 1 ,10797   ,281.1,279,278
XS GIS Cut Line= 6
1591662.34311825460312.7735699271591741.97616109460349.201318592
1591809.79131417460381.2977110891591898.78359026460426.911136925
1591964.19389251460467.0331039281592040.57464525460515.983793423
#Sta/Elev= 30
       0  980.58     8.3  975.88    20.3  972.14    37.2  964.96    52.5  954.63
    64.9  948.13    87.7   930.9   106.9  924.06   145.7  906.04     166  903.38
   171.3   901.5   178.7  896.23   182.4  891.66   197.1  868.86  202.25 865.897
   211.8  865.18  222.06 865.896   230.3  871.09   248.7  877.98   269.7  880.64
   286.6  884.15   321.2  898.71   348.3  907.08   369.1  910.88   381.3  914.75
   389.7  919.32   402.8  928.39   408.7  934.59   418.4  946.33   430.1  958.75
#Mann= 3 ,-1,0
       0      .1       0  202.25    .045       0  222.06      .1       0
Bank Sta=202.25,222.06
XS Rating Curve= 0 ,0
Exp/Cntr(USF)=0,0
Exp/Cntr=0.3,0.1

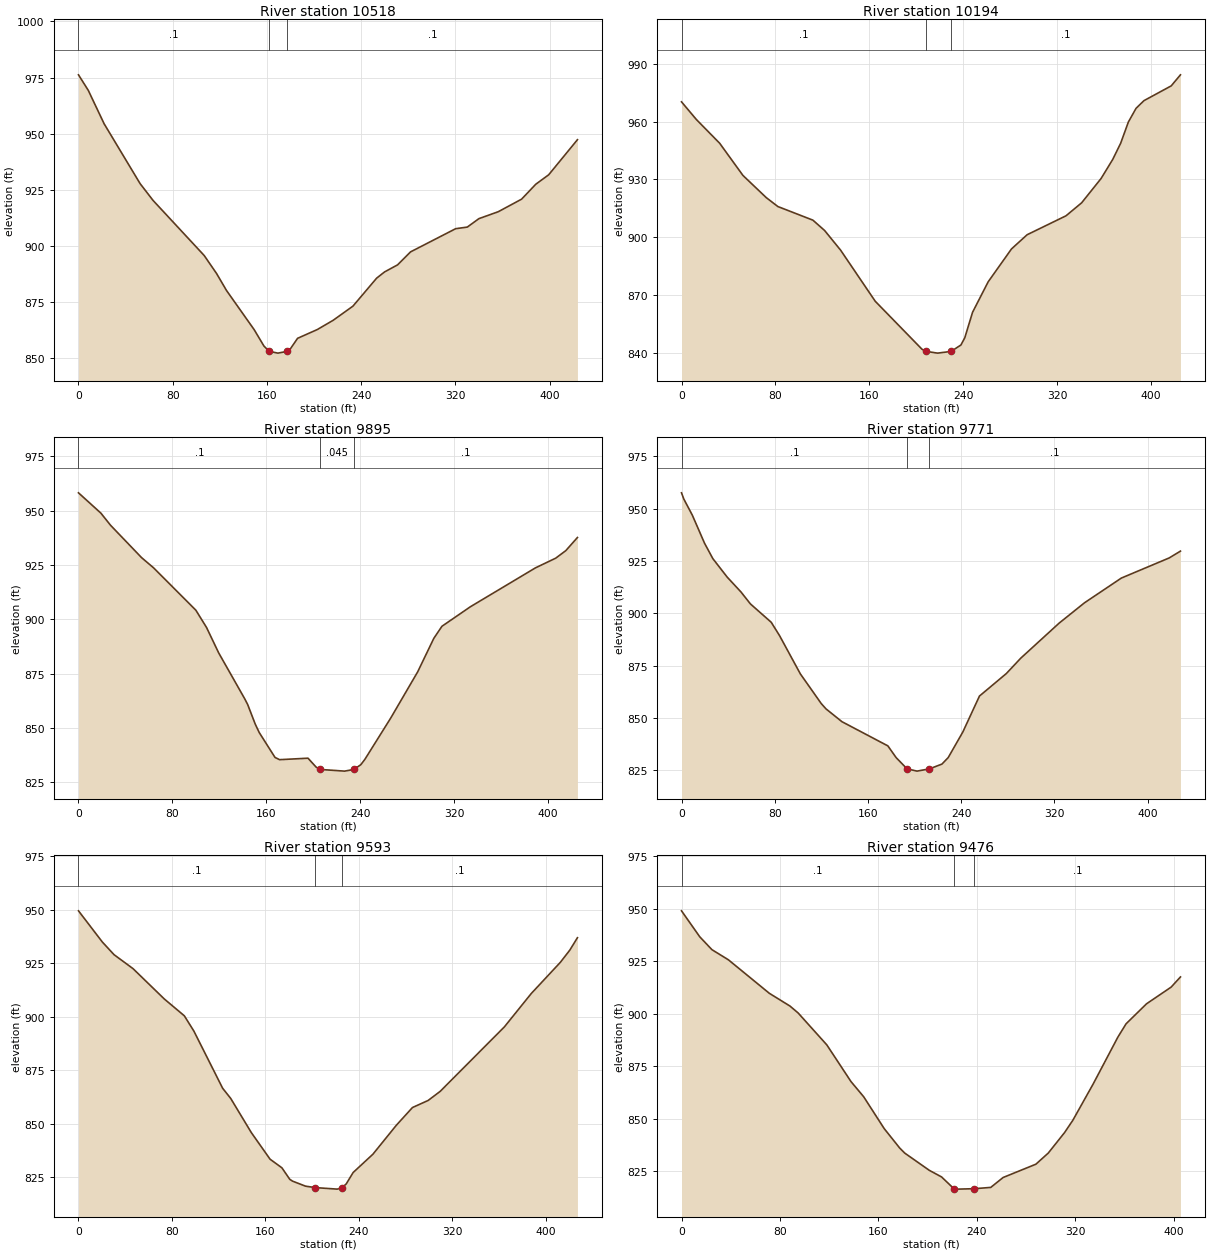
Type RM Length L Ch R = 1 ,10518   ,322.7,323.7,325.1
XS GIS Cut Line= 4
1591540.37493708460596.6019365881591671.24526243 460624.30514544
 1591853.0546791460662.8555469211591956.59417017460672.140305251
#Sta/Elev= 30
       0   976.2     8.3  969.29    21.8  954.34    52.3  927.69    63.3  920.19
   106.7  895.63   117.3  887.53   125.7  879.99   149.2  862.51   157.4  855.28
  161.84852.8813   169.3  852.08  177.28852.8789   179.6  853.77     186  858.68
   202.8  862.61   216.2  866.72     233  873.03   253.1   885.5   259.8  888.28
   270.9  891.44   281.9  897.23   320.2  907.57   330.1   908.3     340  912.07
   356.4  915.15   376.2  920.75   388.2  927.39   399.2  931.62   423.6  947.27
#Mann= 3 ,-1,0
       0      .1       0  161.84    .045       0  177.28      .1       0
Bank Sta=161.84,177.28
XS Rating Curve= 0 ,0
Exp/Cntr(USF)=0,0
Exp/Cntr=0.3,0.1

Type RM Length L Ch R = 1 ,10194   ,305.5,299.2,293.3
XS GIS Cut Line= 6
1591575.32327917460901.8029036671591662.16595326460912.695598423
1591736.34789151460923.7438046781591835.25681442460938.474746332
1591909.43875268460949.5229525861591995.98418325460962.412362501
#Sta/Elev= 30
       0  970.27    12.6  961.14    32.5  948.78    52.3   932.1    72.2  920.56
    82.1  915.93   111.9  908.88   121.9   903.5   135.5  893.32     165   866.8
   204.8  841.91  208.49840.7593   218.1  839.87   229.6  840.76     238  844.09
   241.3  847.86   247.9  861.05   261.2  876.87   281.1  893.96   294.4  901.31
   327.5  911.13   340.8  917.86   357.4   930.5   367.3  940.38     374   948.7
   380.6  959.76   387.2  966.93   393.9  970.89   417.1  978.55     425  984.29
#Mann= 3 ,-1,0
       0      .1       0  208.49    .045       0   229.6      .1       0
Bank Sta=208.49,229.6
XS Rating Curve= 0 ,0
Exp/Cntr(USF)=0,0
Exp/Cntr=0.3,0.1

Type RM Length L Ch R = 1 ,9895    ,124.3,123.7,123.8
XS GIS Cut Line= 6
1591576.26979959461290.1948434261591659.27947609461262.524951249
1591730.43090859461238.8078070881591825.29915717461207.185166925
1591896.45026159461183.4680227491591979.46026617461155.798458666
#Sta/Elev= 30
       0  958.16    19.1  948.81    27.3  943.25    53.7  928.38    64.1   923.6
     100  904.16   109.1  896.21   119.4  884.57   141.5  863.53   144.1  860.82
   150.6  851.74     154  847.88   167.4  836.47   171.3  835.44   195.5  836.12
   202.4  832.03  205.82 830.947   226.6  830.17  234.72 830.948   240.5  833.15
   243.9  835.55     266  854.61   288.9   875.8   302.7  891.27   309.6  896.79
   333.8  905.76   389.2  923.64   406.5  928.11   415.1  931.58     425  937.61
#Mann= 3 ,-1,0
       0      .1       0  205.82    .045       0  234.72      .1       0
Bank Sta=205.82,234.72
XS Rating Curve= 0 ,0
Exp/Cntr(USF)=0,0
Exp/Cntr=0.3,0.1

Type RM Length L Ch R = 1 ,9771    ,175.7,177.5,179.7
XS GIS Cut Line= 3
1591632.04993094461418.7008847461591876.47793192461313.002289725
1592005.66510362461215.377892935
#Sta/Elev= 30
       0  957.56     1.9  954.68     9.3  946.86    19.8  933.44    26.9  926.12
    39.2   917.3    51.1  910.16    59.1  904.51      77  895.72    84.1  889.38
     102  871.06   119.9  856.91     124  854.35   137.7  848.23   177.1  836.68
   184.2  831.07  193.52825.7387   202.1  824.62   212.8  825.71   223.5  827.98
   228.9   831.1   241.4  843.28   255.7  860.48   278.8  871.25   291.1  878.55
     324  895.28   345.9  905.05   377.5  916.85   418.5  926.45   428.2  929.71
#Mann= 3 ,-1,0
       0      .1       0  193.52    .045       0   212.8      .1       0
Bank Sta=193.52,212.8
XS Rating Curve= 0 ,0
Exp/Cntr(USF)=0,0
Exp/Cntr=0.3,0.1

Type RM Length L Ch R = 1 ,9593    ,113.7,117.2,122.1
XS GIS Cut Line= 6
1591688.98906234461535.3793924151591777.86716542461523.966357499
1591850.98020817461507.1445407571591947.84681234461482.307320088
1592020.49660142461463.6790765081592105.25463401461441.946180344
#Sta/Elev= 30
       0  949.59    20.4  935.02    30.4   929.1    46.7  922.55    73.4   908.4
    90.6   900.5    98.8  893.33   123.4  866.62   130.3  861.86     148  845.85
     164  833.44   174.1  829.43   180.9  824.02   183.3  823.17   194.4  820.83
  202.79820.1626   221.5  819.45  225.72820.1621   229.2   821.9   235.1  827.22
     252  835.76   272.1  849.33   285.9  857.61   299.3  860.91   309.6  865.16
   364.6  895.34   387.5  910.87   412.5  925.52   420.6  931.24   427.1  937.01
#Mann= 3 ,-1,0
       0      .1       0  202.79    .045       0  225.72      .1       0
Bank Sta=202.79,225.72
XS Rating Curve= 0 ,0
Exp/Cntr(USF)=0,0
Exp/Cntr=0.3,0.1

Type RM Length L Ch R = 1 ,9476    ,174.2,175.3,178.8
XS GIS Cut Line= 2
1591678.29306626 461571.376633111592077.59886967461642.576381145
#Sta/Elev= 30
       0  949.02    14.8  936.67    24.7  930.52    38.1  925.69    71.4  909.71
    88.1  903.67    94.8  900.35   118.1  885.15   137.8  867.63   148.1  860.41
   164.8  845.21   177.4  835.96   181.4   833.6   201.4  825.37   211.4  822.21
   221.4  816.62   224.7   816.4   238.1  816.61   251.4  817.22   261.4  821.93
   288.1  828.29   298.1  833.56   311.4  843.36   318.1   849.2   334.7  866.57
   354.7  888.82   361.4  895.19     378  904.71     398  912.66   405.6  917.51
#Mann= 3 ,-1,0
       0      .1       0   221.4    .045       0   238.1      .1       0
Bank Sta=221.4,238.1
XS Rating Curve= 0 ,0
Exp/Cntr(USF)=0,0
Exp/Cntr=0.3,0.1

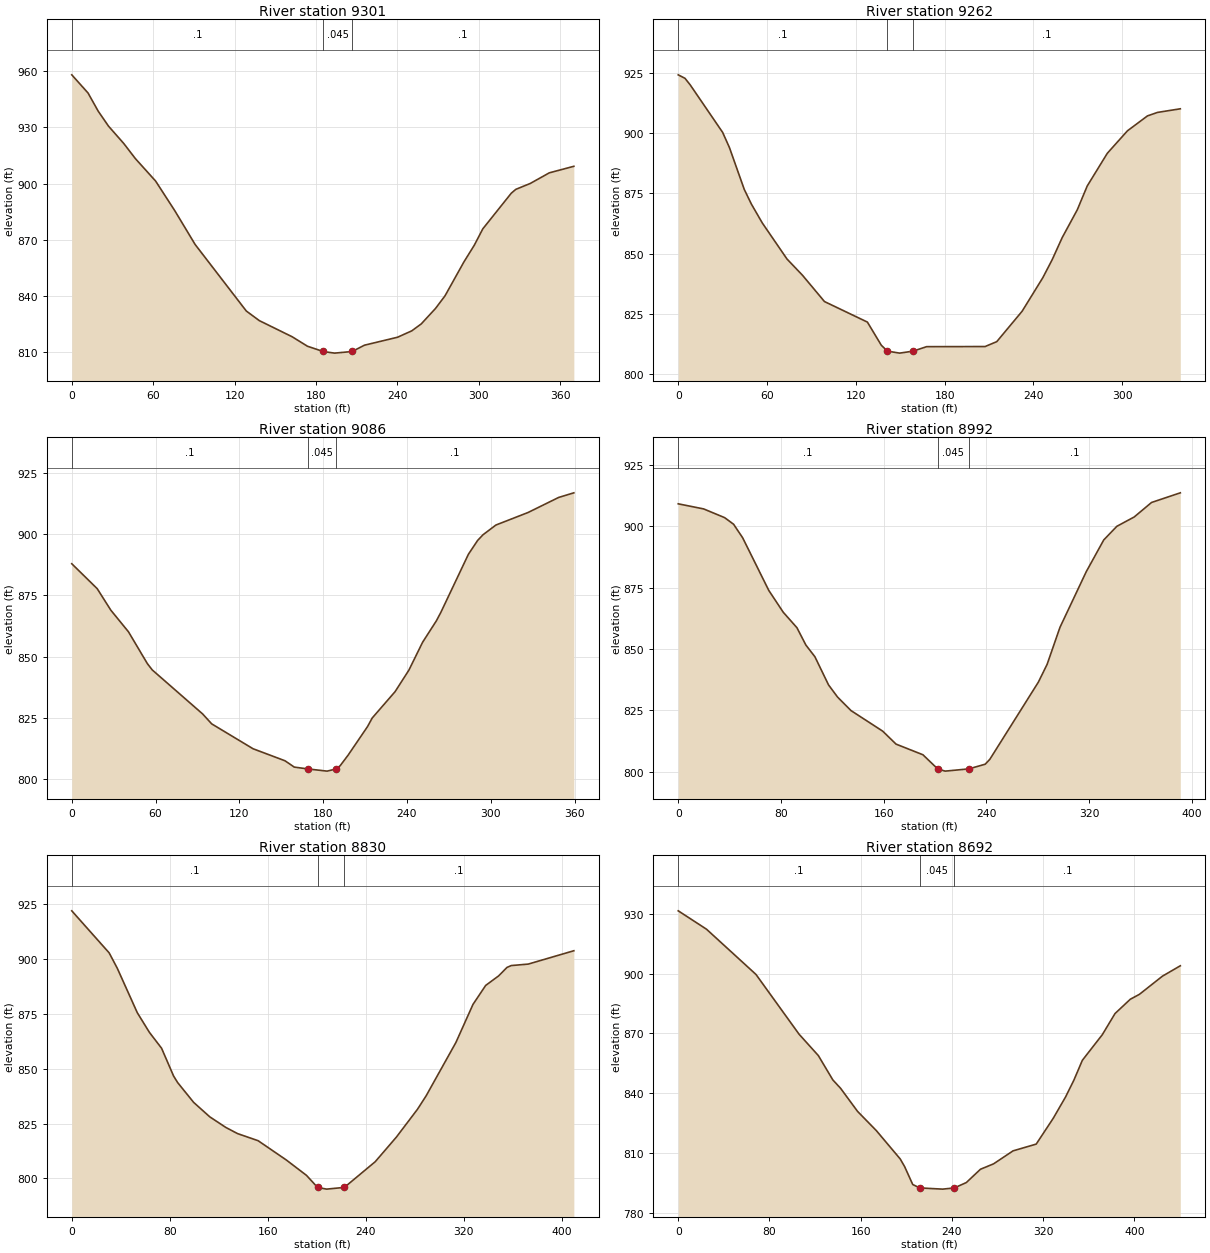
Type RM Length L Ch R = 1 ,9301    ,38.3,38.6,38.4
XS GIS Cut Line= 3
1591643.01811588461663.4491288671591836.36891773461772.087062071
1591975.57227779461823.617460213
#Sta/Elev= 30
       0  958.02      12  948.33    19.5  938.63    27.1  930.65    38.4  921.35
    46.8  913.43    61.8  901.39      76  885.52      91  867.51   128.7  832.06
   138.3  826.94   162.5  818.34   173.8  813.28  185.36810.4795   193.8  809.61
  206.75  810.48   215.8  813.84   240.2  818.08   250.7  821.49   257.7   825.2
   268.2  833.43   275.2  840.16   289.2  858.31   296.8  867.16   303.1  875.91
   324.1  894.92   327.4  896.94   338.1   900.1   352.1  905.75   370.2  909.24
#Mann= 3 ,-1,0
       0      .1       0  185.36    .045       0  206.75      .1       0
Bank Sta=185.36,206.75
XS Rating Curve= 0 ,0
Exp/Cntr(USF)=0,0
Exp/Cntr=0.3,0.1

Type RM Length L Ch R = 1 ,9262    ,177.9,175.8,172.2
XS GIS Cut Line= 3
 1591649.3340743461720.6685484151591850.50900898461815.150067259
1591963.62973903461844.715712611
#Sta/Elev= 30
       0  924.19     4.6  922.73     8.2  919.92      30  900.32    34.6  894.01
    44.6  876.68    49.4   870.6    56.8  862.74    73.5  847.78      84  841.02
    98.8  830.15   127.8  821.63   137.2  812.03   141.3 809.595   149.6  808.76
  158.73809.5934   167.8  811.44   207.3  811.49   215.2  813.52   232.3  826.11
   246.3  840.03   252.6  847.47   259.4  856.67   269.6  868.21   276.3  878.07
   289.9  891.66   303.5  900.97     317  907.15   323.8   908.6   339.2   910.1
#Mann= 3 ,-1,0
       0      .1       0   141.3    .045       0  158.73      .1       0
Bank Sta=141.3,158.73
XS Rating Curve= 0 ,0
Exp/Cntr(USF)=0,0
Exp/Cntr=0.3,0.1

Type RM Length L Ch R = 1 ,9086    ,98.3,94.6,89.7
XS GIS Cut Line= 2
1591628.76666884461934.6981115111591988.05353301461945.624545663
#Sta/Elev= 30
       0  887.91    18.2  877.75      28  868.94    40.6  860.14    54.1  847.19
    57.6   844.6    93.7  826.63   100.2  822.58   129.8  812.43   152.7  807.52
   159.3  804.95  169.21804.1818   182.8   803.3  189.29 804.183   192.1  805.46
   197.8  809.76   211.8  821.49   215.1  824.95   231.5  835.72   241.4  844.51
   251.2  855.87   261.1  864.65   264.3   868.1     284  891.77   290.6  897.41
   294.5  899.75   303.7   903.7   326.7  908.81   348.6  914.95   359.5  916.84
#Mann= 3 ,-1,0
       0      .1       0  169.21    .045       0  189.29      .1       0
Bank Sta=169.21,189.29
XS Rating Curve= 0 ,0
Exp/Cntr(USF)=0,0
Exp/Cntr=0.3,0.1

Type RM Length L Ch R = 1 ,8992    ,157.5,161.5,163.5
XS GIS Cut Line= 6
1591613.22773093462108.7903190851591694.88307942462077.347140506
1591764.87309693462050.3957508361591859.33977151462017.436827257
1591933.20510934461997.8036644161591983.61747261461985.435509577
#Sta/Elev= 30
       0  909.12    19.8  907.04    36.1   903.5    43.1   900.8    50.2  895.25
    70.5  873.84    81.8  864.92    92.4  858.66    99.4  851.57   106.4  846.83
     117  835.37     124  830.42   134.5  824.89   159.2   816.5   169.6  811.22
   190.5  806.89  201.99801.1322   207.8  800.22  226.24801.1329     239  803.04
   242.6  805.03   280.4  836.49   287.2  843.72   297.2  858.79   317.7   881.5
   331.3  894.41   341.5  899.96     355  903.76   368.5  909.67   390.9   913.6
#Mann= 3 ,-1,0
       0      .1       0  201.99    .045       0  226.24      .1       0
Bank Sta=201.99,226.24
XS Rating Curve= 0 ,0
Exp/Cntr(USF)=0,0
Exp/Cntr=0.3,0.1

Type RM Length L Ch R = 1 ,8830    ,141.8,137.9,125
XS GIS Cut Line= 3
1591642.68444177462197.2365748321591888.66807191462183.129986723
1592042.95887935462129.348619558
#Sta/Elev= 30
       0  921.93    30.5  902.78    37.1  895.82    53.5  875.48    63.4  866.52
    73.3  859.31    83.1  846.66    86.4  843.67    99.5  834.62   112.7  828.02
   125.8   823.2   135.3  820.41   152.1  817.17   175.1  808.39   191.6  801.36
  200.59795.8884     208   795.1   222.5  795.89   247.7   807.6   264.9  818.77
   282.2  831.51   289.2  837.58   313.5  861.89   327.5   879.3   337.8  887.91
   348.5  892.32   355.2  896.12   358.7  896.98   372.6  897.66   409.8  903.74
#Mann= 3 ,-1,0
       0      .1       0  200.59    .045       0   222.5      .1       0
Bank Sta=200.59,222.5
XS Rating Curve= 0 ,0
Exp/Cntr(USF)=0,0
Exp/Cntr=0.3,0.1

Type RM Length L Ch R = 1 ,8692    ,66.7,66.3,66.7
XS GIS Cut Line= 6
1591692.05828193462420.5078715091591780.68638551462394.616847172
1591838.83193851462347.2448946681591917.88460192462285.577367082
1591986.72567159462248.0036233371592073.75699359462211.497462749
#Sta/Elev= 30
       0  931.59    24.8  922.36    68.2  899.64     106  869.62   122.9   858.9
   135.6  846.68   142.4  842.47   157.3  830.87   173.7  821.26   194.7  806.99
   198.6  803.12   205.7  794.14  211.92792.4308   231.9  791.83  242.18792.4306
   252.7  795.13   265.1  801.81   276.6  804.52   293.7  811.05     314  814.44
   328.9  827.37   339.7  838.06     347  846.49   354.5  856.55     372   869.4
   383.1  879.98   396.5  887.17   404.5  889.64   424.7  898.77   440.4  903.99
#Mann= 3 ,-1,0
       0      .1       0  211.92    .045       0  242.18      .1       0
Bank Sta=211.92,242.18
XS Rating Curve= 0 ,0
Exp/Cntr(USF)=0,0
Exp/Cntr=0.3,0.1

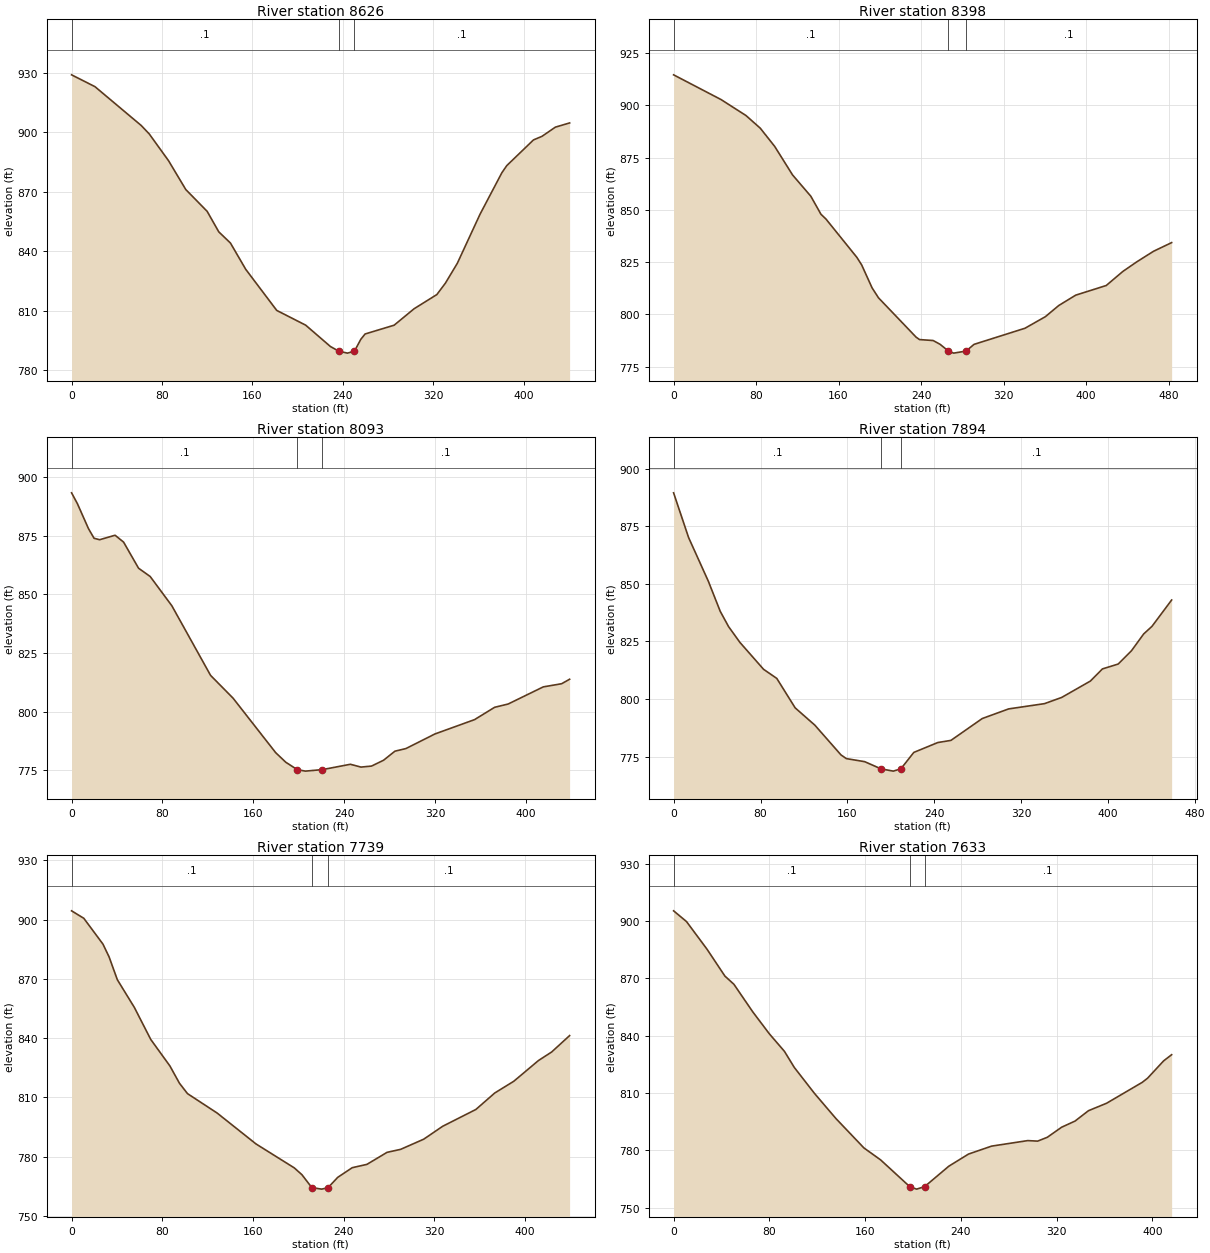
Type RM Length L Ch R = 1 ,8626    ,226.4,228.5,236.7
XS GIS Cut Line= 3
1591702.51566095462442.656024012 1591889.6902563462386.870654417
1592093.74726613462250.343302515
#Sta/Elev= 30
       0  928.94    20.7  922.98    61.6  903.42    68.7  899.18    85.8  885.68
   101.1  871.11     120  860.13   130.3  849.78   140.6  844.16   154.2  830.86
   181.6  810.18   207.2  802.75   229.1  791.99  236.43789.6511   244.2  788.65
   250.4  789.65     256  795.61   259.8   798.3   285.5  802.73   303.2  811.03
   323.3  818.17   330.8  823.86   341.4   833.9   361.5  858.64   380.9  879.64
   385.2  883.18   408.8  896.12   416.4  897.95   428.2  902.56   440.8  904.69
#Mann= 3 ,-1,0
       0      .1       0  236.43    .045       0   250.4      .1       0
Bank Sta=236.43,250.4
XS Rating Curve= 0 ,0
Exp/Cntr(USF)=0,0
Exp/Cntr=0.3,0.1

Type RM Length L Ch R = 1 ,8398    ,303.7,304.2,313.8
XS GIS Cut Line= 6
1591724.98800609462488.8709237581591846.54583384462531.342623591
  1591927.140817462574.2798736691592026.88274351  462585.6492735
1592101.84847283462587.9209225031592189.30827168462590.570851594
#Sta/Elev= 30
       0  914.61    46.1  902.75    70.2  895.13    84.1  889.05      98  880.38
   115.4  866.68   133.1  856.49   142.9  847.89   147.8  845.57   177.7  827.27
   182.4  823.63   192.5  812.64   198.7  807.89   235.2  789.05   238.5   787.9
   251.7  787.44   258.4  785.65   266.6782.3821   271.6  781.41  283.58782.3792
   291.4  785.61   340.8  793.32   360.5  798.84   373.6  804.22     390  809.16
   419.6  813.78   435.7  820.51   449.3  825.13   465.5  830.17     483   834.3
#Mann= 3 ,-1,0
       0      .1       0   266.6    .045       0  283.58      .1       0
Bank Sta=266.6,283.58
XS Rating Curve= 0 ,0
Exp/Cntr(USF)=0,0
Exp/Cntr=0.3,0.1

Type RM Length L Ch R = 1 ,8093    ,196.4,199.3,199.3
XS GIS Cut Line= 6
1591591.02698793462564.2123085111591649.64891793462629.171824262
1591699.89619276462684.8515029251591766.89244984462759.090855762
 1591817.8657731462817.9240714161591882.89484251462891.399646252
#Sta/Elev= 30
       0   893.3     5.1  888.72    14.9  878.02    19.8  873.93    24.7  873.31
    38.3  875.22    45.8  872.29      59  861.15    69.2  857.64    88.3  845.15
   122.4  815.47   142.2  805.76   179.7  782.54   188.6  778.46  198.62775.3102
   205.9  774.66  220.89775.3082   245.5  777.58   254.8  776.38   264.1  776.81
   274.7   779.3   284.7  783.16   294.4  784.28     320  790.52   354.8  796.61
   372.5  801.87   384.4  803.27   415.3  810.57   431.5  811.92   438.5  813.83
#Mann= 3 ,-1,0
       0      .1       0  198.62    .045       0  220.89      .1       0
Bank Sta=198.62,220.89
XS Rating Curve= 0 ,0
Exp/Cntr(USF)=0,0
Exp/Cntr=0.3,0.1

Type RM Length L Ch R = 1 ,7894    ,162,155.6,150
XS GIS Cut Line= 3
1591463.85106072462773.8612665891591610.65466492462843.592978582
1591757.45826912463100.499285924
#Sta/Elev= 30
       0  889.56    13.8  870.14      32  851.14    42.9  838.11    50.6  831.45
      61  824.61    82.8   812.9      95  808.93   111.9  796.14     130  788.64
   154.1  775.69     159   774.1   175.9  772.77   190.9  769.65   202.2  768.66
   209.2  769.66   221.1  776.79   243.2  781.08   255.3  782.02   284.1  791.51
   308.4  795.69   341.4  797.98   357.2  800.67   383.6  807.78   394.7  813.06
   409.2  815.18   421.4  820.94   432.7  828.27   440.3  831.55   458.4  842.99
#Mann= 3 ,-1,0
       0      .1       0   190.9    .045       0   209.2      .1       0
Bank Sta=190.9,209.2
XS Rating Curve= 0 ,0
Exp/Cntr(USF)=0,0
Exp/Cntr=0.3,0.1

Type RM Length L Ch R = 1 ,7739    ,102.6,105.2,108.4
XS GIS Cut Line= 4
1591376.04841526462872.7717307511591527.71062855462995.534708924
1591580.55992606 463014.61917747 1591728.1936451   463131.316657
#Sta/Elev= 30
       0  904.49    10.8  900.71    27.7  887.65    33.1  881.18    40.4  869.61
    55.4   855.6    69.9  839.36    86.8  825.94    95.2  817.21   102.3  811.95
   128.4  802.14   162.8  786.46   196.5  774.37   203.3  770.89  212.05 764.345
   220.7   763.6  226.29764.3161   234.9  769.57   247.7  774.46   260.6  776.12
   278.4  782.22   290.4  783.74   310.8  788.89   327.5  795.42   356.8  803.93
   373.5  812.29   390.3  818.23     412  828.69   423.7  833.04   439.5  841.33
#Mann= 3 ,-1,0
       0      .1       0  212.05    .045       0  226.29      .1       0
Bank Sta=212.05,226.29
XS Rating Curve= 0 ,0
Exp/Cntr(USF)=0,0
Exp/Cntr=0.3,0.1

Type RM Length L Ch R = 1 ,7633    ,137.6,137.6,137.6
XS GIS Cut Line= 2
1591327.93119459462939.5957740591591632.10450068463223.490859749
#Sta/Elev= 30
       0  905.41    10.8  899.78      28  885.25    42.9  871.22    50.4  866.95
    66.1  852.55      80  841.01    92.6  831.84   100.9  823.36   117.7  809.82
   135.7   796.6     159  781.27   172.9  775.03  197.28761.0032     203  759.69
   209.7760.9775   229.9  771.67   246.4  778.05   265.7  782.21   295.9   785.1
   304.1  784.82   312.2  786.82   324.2  792.11   335.4  795.32   346.6  800.75
   361.8  804.67   391.5  815.58     396  817.77   409.4  826.84   416.1  830.07
#Mann= 3 ,-1,0
       0      .1       0  197.28    .045       0   209.7      .1       0
Bank Sta=197.28,209.7
XS Rating Curve= 0 ,0
Exp/Cntr(USF)=0,0
Exp/Cntr=0.3,0.1

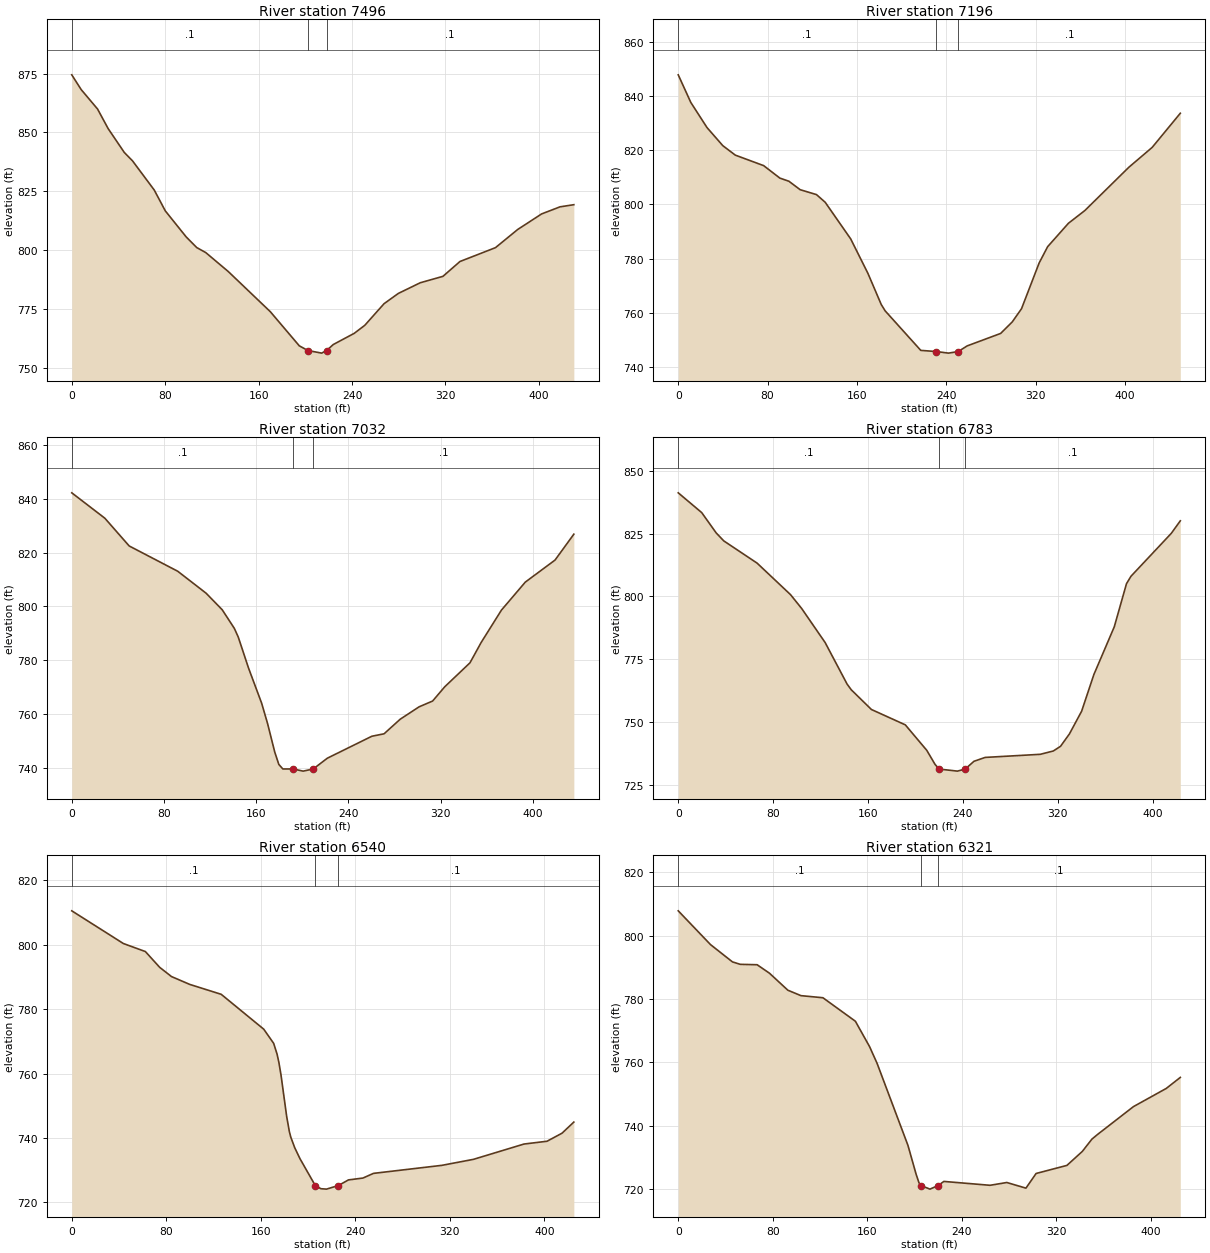
Type RM Length L Ch R = 1 ,7496    ,301.4,300,304.2
XS GIS Cut Line= 6
1591227.60612684463033.5932594981591291.46787576463093.409412846
1591346.20628335463144.6799795931591419.19104551463213.041391417
1591479.19420634463258.6915625931591562.46766184463297.782363668
#Sta/Elev= 30
       0  874.45     8.1  868.15    22.1  859.91    31.1  851.64      45  841.45
      52  837.91    70.6  825.52    80.1  816.64      98  805.57     107  801.06
   114.7  798.94     134  790.88     170  773.82   194.8  759.32  202.16757.3192
     214  756.21   218.2757.3174   223.9  759.86   241.9  764.63   250.9  768.03
   267.4  777.21   279.6  781.57   298.4  786.11   317.8  788.83   332.4  795.14
   362.8  801.02   381.8  808.73   402.3  815.35   418.1  818.37   429.9  819.27
#Mann= 3 ,-1,0
       0      .1       0  202.16    .045       0   218.2      .1       0
Bank Sta=202.16,218.2
XS Rating Curve= 0 ,0
Exp/Cntr(USF)=0,0
Exp/Cntr=0.3,0.1

Type RM Length L Ch R = 1 ,7196    ,164.9,163.4,158.1
XS GIS Cut Line= 6
1591111.81666026463327.2301394191591203.09830184463370.160827845
1591280.97183375463407.1253208371591352.18921101463477.325639755
1591405.60216193463529.976125002  1591467.917326463591.401199013
#Sta/Elev= 30
       0  847.79    11.3  837.58    25.8  828.32    39.9  821.67    51.1  818.17
    76.5   814.3      91   809.7    99.1  808.54   109.2  805.42   123.8  803.61
   131.6  800.78   154.5  787.23   169.8  774.62   181.8  763.07   185.3  760.73
   217.2  746.15     231  745.73     242  745.14  250.79745.7281   258.7   747.8
   288.7   752.4   299.1  756.65   307.4  761.51   323.2   778.4   330.8   784.4
   349.4  793.03   364.1  797.73   403.5  813.69   424.4  821.02   449.6  833.62
#Mann= 3 ,-1,0
       0      .1       0     231    .045       0  250.79      .1       0
Bank Sta=231,250.79
XS Rating Curve= 0 ,0
Exp/Cntr(USF)=0,0
Exp/Cntr=0.3,0.1

Type RM Length L Ch R = 1 ,7032    ,247.6,249.7,253.3
XS GIS Cut Line= 3
1591019.66403145463479.8841112711591345.03969303463603.279205696
1591426.44307354463635.368708448
#Sta/Elev= 30
       0  842.16    28.7  832.74    49.8  822.45    91.9  813.07   116.5  804.93
   130.5  798.78     141  791.89   144.4  788.67   153.3  777.19   164.7  764.12
   169.8  756.63   176.1  745.94   179.6  741.41   183.1  739.72  191.89739.7183
   200.7  738.92  209.42739.7119   221.7  743.72   260.3  751.86   270.9  752.77
   284.9  758.18   301.3  762.78     313  764.92   323.5   770.2   345.4   779.1
   355.1  786.64   372.7  798.65   393.4  809.04   419.2  817.22   435.5  826.82
#Mann= 3 ,-1,0
       0      .1       0  191.89    .045       0  209.42      .1       0
Bank Sta=191.89,209.42
XS Rating Curve= 0 ,0
Exp/Cntr(USF)=0,0
Exp/Cntr=0.3,0.1

Type RM Length L Ch R = 1 ,6783    ,241.8,242.6,246.4
XS GIS Cut Line= 3
1590942.10821442463640.6959776861591203.96175619463835.543225939
1591296.53624065463864.638063913
#Sta/Elev= 30
       0  841.24    19.8  833.37      32  825.29    38.4  822.12    66.5  813.27
    94.7  800.73   104.1  795.21   123.9  781.66   142.4  765.14   145.9  762.88
   162.9  755.04   191.5  748.92   209.6  738.78   216.6  733.17  220.05731.3318
   235.4  730.51  241.97731.3334   249.4  734.42   258.8  735.96   305.3   737.2
   316.3  738.52   322.4  740.39   329.9  745.32   340.2  754.37   350.5  768.93
   367.7  787.91     378  805.07   381.8  808.04   415.8  825.12   423.4   830.1
#Mann= 3 ,-1,0
       0      .1       0  220.05    .045       0  241.97      .1       0
Bank Sta=220.05,241.97
XS Rating Curve= 0 ,0
Exp/Cntr(USF)=0,0
Exp/Cntr=0.3,0.1

Type RM Length L Ch R = 1 ,6540    ,219.9,219.5,218.3
XS GIS Cut Line= 6
1590781.14944321463751.077977931 1590838.6099582463817.105733012
1590889.08787562463872.576750686 1590956.6609032463946.291826343
1591007.34059187464001.578133098 1591066.4677702464066.078004097
#Sta/Elev= 30
       0   810.5    43.7  800.35    62.3  797.86    74.4  792.97    84.4   790.1
    99.9  787.66   126.5  784.59   162.5  773.77   170.9  769.37   173.8  766.02
   175.3  763.49   177.1   759.6   181.9  746.72   184.2  741.96   185.4  740.27
   188.7  737.01   193.1  733.63  206.11725.2491   210.9  724.26   215.6  724.13
  225.73725.2488   234.2  726.99   246.5  727.57   255.4  729.02   313.3  731.51
     340  733.37   382.8  738.12   402.3  738.99     415  741.49     425  744.94
#Mann= 3 ,-1,0
       0      .1       0  206.11    .045       0  225.73      .1       0
Bank Sta=206.11,225.73
XS Rating Curve= 0 ,0
Exp/Cntr(USF)=0,0
Exp/Cntr=0.3,0.1

Type RM Length L Ch R = 1 ,6321    ,77.4,79.4,82.7
XS GIS Cut Line= 6
1590607.90240462463917.8756226461590671.95739463463977.573994057
1590727.21220538464028.3386563081590802.68941663464093.937278391
1590859.42453937464142.9896737351590925.61600805 464200.21692148
#Sta/Elev= 30
       0  807.83    27.3  797.18    45.9  791.71    52.5  790.94    66.8  790.81
    77.3  788.12    92.8  782.77   103.9  781.05   122.5  780.39     150  772.97
     162  764.96   168.4  759.65   194.5  733.78   201.5  724.56   203.8  722.01
   205.5 721.112   213.1  719.97  220.05  721.09   224.9   722.4     264  721.18
   278.2  722.06   294.4  720.28     303  724.91   329.1  727.46   342.1  731.86
   350.3  735.77     355  737.22   385.4  746.01   413.2  751.76   425.1  755.24
#Mann= 3 ,-1,0
       0      .1       0   205.5    .045       0  220.05      .1       0
Bank Sta=205.5,220.05
XS Rating Curve= 0 ,0
Exp/Cntr(USF)=0,0
Exp/Cntr=0.3,0.1