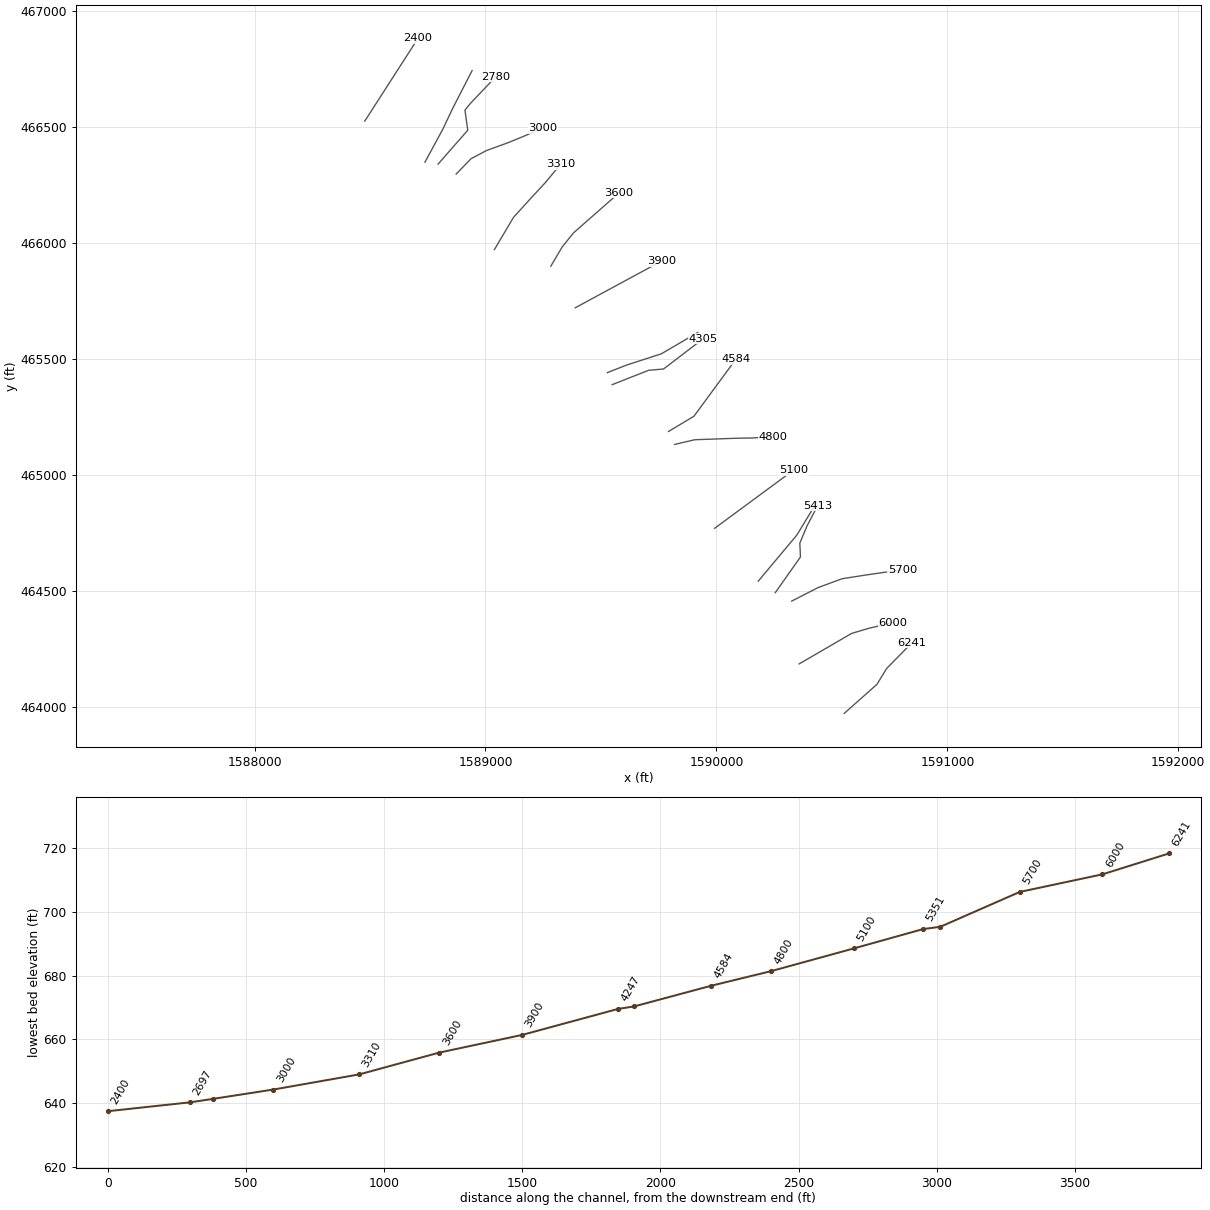
HEC-RAS study SimsRn.prj: SimsRn

--- SimsRn.g01 (geometry) --- (continued)

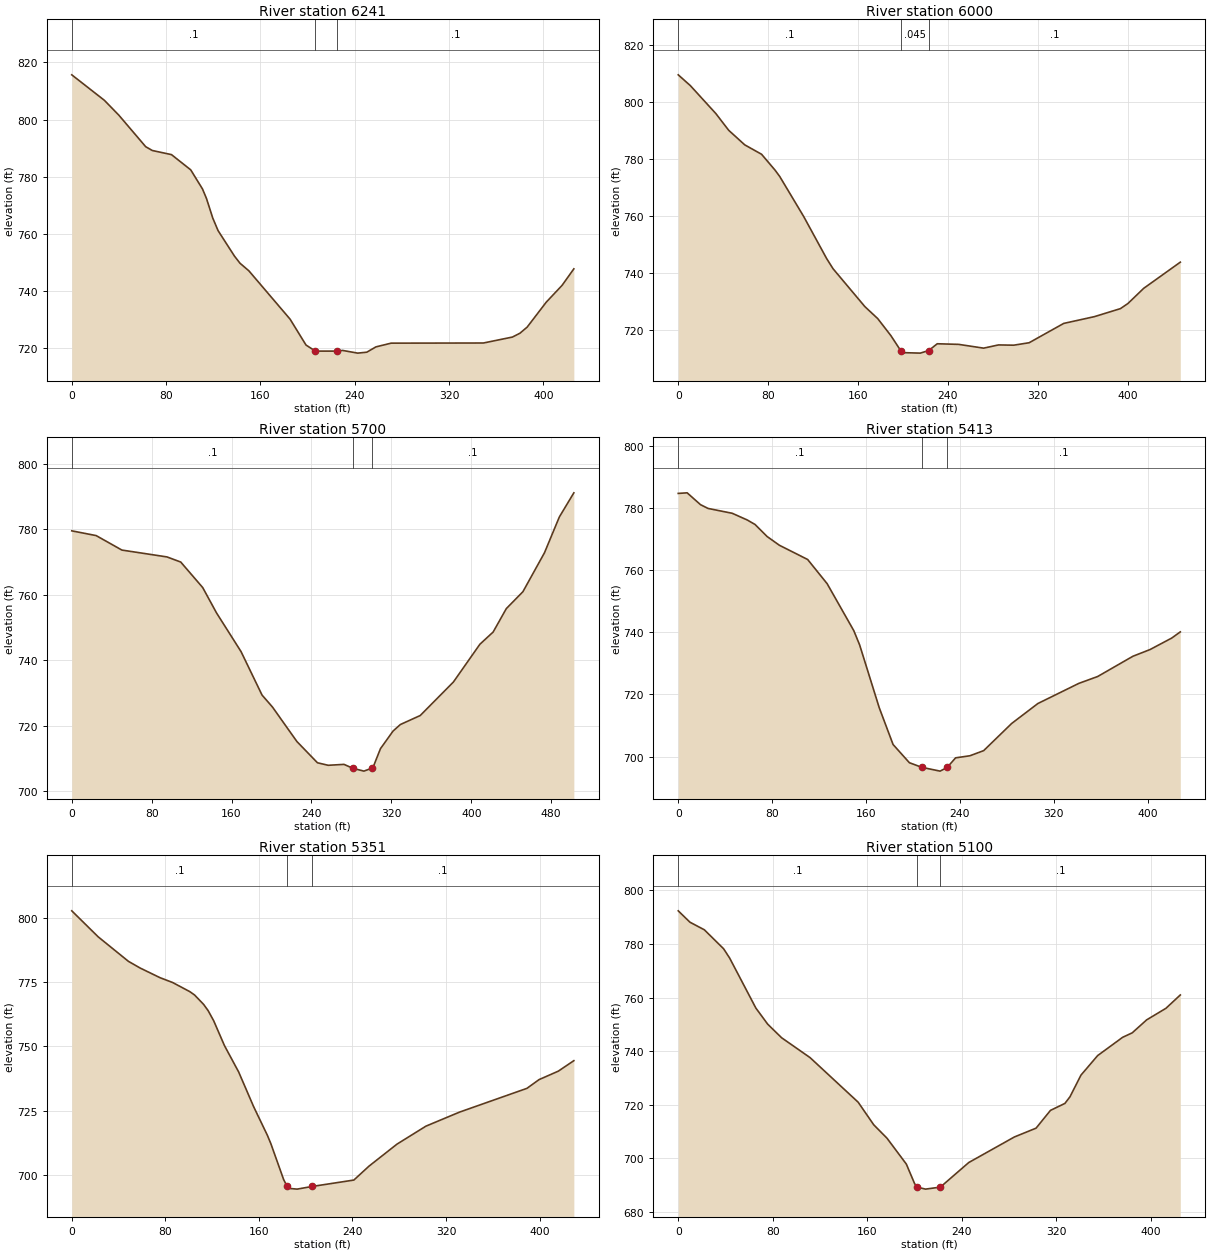
Type RM Length L Ch R = 1 ,6241    ,246.7,241.2,235.7
XS GIS Cut Line= 4
1590553.29537967463970.4374747291590695.24292252464095.633444195
1590736.68102509464163.5213994691590846.88874469464275.492442582
#Sta/Elev= 30
       0  815.63    27.7   806.7    39.9  801.53    62.7  790.49    68.3  789.16
    84.6  787.71   100.9  782.39   110.9  775.69   114.3  772.34   119.6  765.53
   124.1  761.13     138  752.22   142.7  749.72   150.2  747.08   185.2  730.15
   198.7   721.1  206.69718.9733  224.99718.9751   229.8  719.21   242.6  718.27
   250.3   718.6     258  720.45   270.9  721.76   349.2  721.81   373.8  723.89
   380.2  725.24   386.3  727.37   402.5   736.1   415.9  741.97   425.9  747.75
#Mann= 3 ,-1,0
       0      .1       0  206.69    .045       0  224.99      .1       0
Bank Sta=206.69,224.99
XS Rating Curve= 0 ,0
Exp/Cntr(USF)=0,0
Exp/Cntr=0.3,0.1

Type RM Length L Ch R = 1 ,6000    ,306.1,299.5,293.8
XS GIS Cut Line= 6
1590358.09211785464183.6792139261590433.81670393464227.520005509
1590498.72372635464265.0976862611590585.26620418464315.201260582
1590664.12956351464338.448261335  1590763.863616464361.161142424
#Sta/Elev= 30
       0  809.53    10.8  805.73    33.5  795.91    44.9  790.05    59.2  784.92
    74.2  781.61    86.2  776.03    90.4  773.78   111.6   759.8   132.1  744.98
   137.8   741.4   166.2  728.05   177.6  723.86   189.4  717.83  197.99712.6393
   200.3  711.89   215.5  711.72  223.02  712.64   230.6  715.01   249.6   714.8
   271.9  713.47   285.1   714.6   298.7  714.51   312.4  715.37   343.2  722.16
   370.6  724.55   393.7  727.36   400.4  729.17   414.4  734.49     447  743.69
#Mann= 3 ,-1,0
       0      .1       0  197.99    .045       0  223.02      .1       0
Bank Sta=197.99,223.02
XS Rating Curve= 0 ,0
Exp/Cntr(USF)=0,0
Exp/Cntr=0.3,0.1

Type RM Length L Ch R = 1 ,5700    ,272,287.5,301
XS GIS Cut Line= 6
1590325.98063351464454.647832096 1590440.6519921464513.044696927
 1590544.3407611464551.125985593 1590644.1673331464566.585928425
1590718.38667284464577.3801981661590804.97541042464589.974004999
#Sta/Elev= 30
       0  779.53    24.4  778.08    50.2  773.66    95.3  771.57   109.1  770.01
   131.1  762.22   144.9   754.5   169.5  742.67   190.5  729.42     201  725.74
   225.4  715.24     246  708.75   256.7  707.98   272.6  708.26  281.36707.0747
   292.5   706.2  300.21707.0738   302.5  708.01   309.1  713.06   321.7  718.43
     329  720.42   348.9  723.17   382.1  733.39   408.6  744.91   421.9  748.65
   435.1   755.8   451.7  760.95   473.3  772.84   488.2  783.77   502.7  791.13
#Mann= 3 ,-1,0
       0      .1       0  281.36    .045       0  300.21      .1       0
Bank Sta=281.36,300.21
XS Rating Curve= 0 ,0
Exp/Cntr(USF)=0,0
Exp/Cntr=0.3,0.1

Type RM Length L Ch R = 1 ,5413    ,69,62.3,53.4
XS GIS Cut Line= 5
1590254.74166782464490.7424928671590363.83178536464644.888273191
1590361.10599549464704.5890503971590393.22863465464780.813307404
1590438.57007941464866.132690564
#Sta/Elev= 30
       0  784.77     7.6  784.96      19  781.14    25.4  779.93      46  778.37
    58.7  776.23    65.4  774.78    75.8  770.87    86.2  768.07   110.3  763.48
   126.9  755.69   149.6  740.57   154.6  735.96   171.3  715.73   183.1  703.87
     197     698  207.75696.4957   223.2  695.29  229.23696.4969   236.4  699.57
   248.6  700.24   260.3  701.89   284.2  710.65   306.5  717.07   341.4  723.56
   357.5  725.78   387.5   732.3   402.1  734.46   420.6  738.17   427.9  740.15
#Mann= 3 ,-1,0
       0      .1       0  207.75    .045       0  229.23      .1       0
Bank Sta=207.75,229.23
XS Rating Curve= 0 ,0
Exp/Cntr(USF)=0,0
Exp/Cntr=0.3,0.1

Type RM Length L Ch R = 1 ,5351    ,252.6,250.7,247.5
XS GIS Cut Line= 3
 1590181.0739521464540.5080289771590348.50151972464739.675419838
1590436.57952922464884.091615602
#Sta/Elev= 30
       0   802.6    22.6   792.5    48.4  783.01    58.4  780.41    75.4  776.66
    86.3  774.76   100.9  771.24     105  769.93   112.7   766.3   116.6  763.86
   121.3  759.97   130.6  750.25   142.7  740.05   155.5  726.59   167.2  715.52
   170.2  712.26   181.2  698.24  184.19 695.594   186.5  694.83   192.7  694.57
  205.41695.5958   241.2  698.09   254.1  703.47     278  712.01   302.8  719.01
   331.6  724.47   389.2  733.69   399.5  737.07     416  740.36   429.3  744.43
#Mann= 3 ,-1,0
       0      .1       0  184.19    .045       0  205.41      .1       0
Bank Sta=184.19,205.41
XS Rating Curve= 0 ,0
Exp/Cntr(USF)=0,0
Exp/Cntr=0.3,0.1

Type RM Length L Ch R = 1 ,5100    ,305.5,300,294.3
XS GIS Cut Line= 6
1589992.00557968464768.3283070921590062.54218401464820.105106428
1590123.00203684464864.4852669981590203.61539267464923.659033179
 1590264.0752455464968.0391937491590334.61184984465019.815993086
#Sta/Elev= 30
       0   792.4     9.9  788.16    22.1  785.32    38.4  778.24    43.5  774.78
    65.7  756.11    75.7   750.1    87.5  745.02   111.6   737.6   152.3  720.96
   165.5  712.52   176.7  707.53   193.1  697.85   200.1  690.54  202.37 689.255
   209.3  688.51  221.88689.2563   245.9  698.43   284.6  707.99   302.9  711.27
   315.1  717.91   327.3   720.5   331.6  722.98   340.9  731.06     355  738.35
   376.2  745.19   384.3  746.85   396.5  751.69   412.8     756     425  760.99
#Mann= 3 ,-1,0
       0      .1       0  202.37    .045       0  221.88      .1       0
Bank Sta=202.37,221.88
XS Rating Curve= 0 ,0
Exp/Cntr(USF)=0,0
Exp/Cntr=0.3,0.1

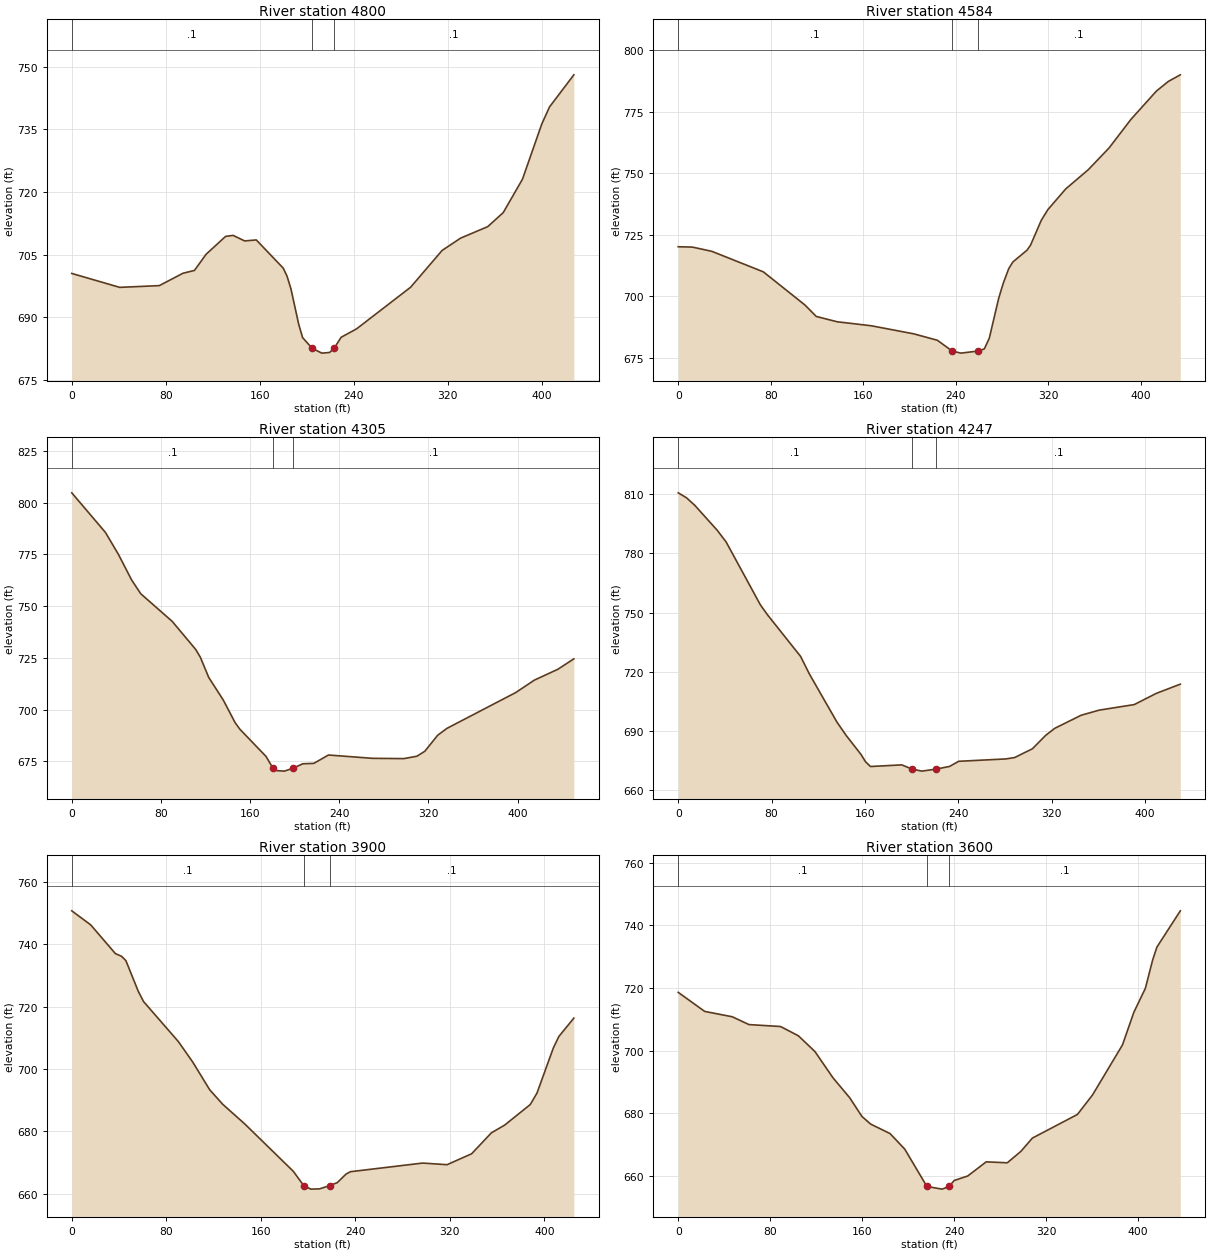
Type RM Length L Ch R = 1 ,4800    ,208.6,216.3,227.3
XS GIS Cut Line= 6
1589819.14601725465130.0818486661589905.97688034465150.373146668
1589980.92915826465153.0503066781590080.86531009465156.619853333
1590155.86155118465158.0676850831590243.68683484465163.427910596
#Sta/Elev= 30
       0  700.48    40.8  697.14    74.5  697.56    94.6  700.52   104.4   701.2
   114.3  705.07   130.9  709.36   137.3   709.6   147.1  708.27     157  708.51
   179.9  701.76   183.2   699.8   186.5  696.77   193.1  688.29   196.4   685.1
  204.59682.5247   212.8  681.38   219.3  681.53  223.23682.5255   229.2  685.18
   242.3  687.19   288.3  697.17   315.1  705.99   330.9  708.95   353.9  711.69
   367.1  715.05   383.5  723.07   399.9  736.28   406.5  740.38   427.2  748.08
#Mann= 3 ,-1,0
       0      .1       0  204.59    .045       0  223.23      .1       0
Bank Sta=204.59,223.23
XS Rating Curve= 0 ,0
Exp/Cntr(USF)=0,0
Exp/Cntr=0.3,0.1

Type RM Length L Ch R = 1 ,4584    ,292.6,278.9,278.3
XS GIS Cut Line= 3
1589792.52331501465185.9565989231589902.72169746465251.806876534
  1590084.364996465497.832998231
#Sta/Elev= 30
       0  720.07    12.3  719.93    29.1  718.21    73.6  709.87   109.5  696.42
   119.4  691.73   137.4  689.57     167  687.94   203.7  684.66   224.1  682.05
  236.96677.6525   244.5  676.82  259.01677.6518   264.7  678.53     269  682.88
   277.1  699.05     281  705.12   285.8  711.15   289.4  713.89   301.6  718.67
   304.6  720.64     314  730.86   319.7  735.19   335.1  743.59   354.6   751.4
   372.6  760.25   391.5  771.86   413.6  783.41   423.9  787.31   434.2  789.98
#Mann= 3 ,-1,0
       0      .1       0  236.96    .045       0  259.01      .1       0
Bank Sta=236.96,259.01
XS Rating Curve= 0 ,0
Exp/Cntr(USF)=0,0
Exp/Cntr=0.3,0.1

Type RM Length L Ch R = 1 ,4305    ,55.7,57.8,60.6
XS GIS Cut Line= 4
1589548.65797395465387.9613096141589706.56359459465449.853964941
1589770.83673666465455.4084340091589943.02527776465586.335204894
#Sta/Elev= 30
       0   804.7    30.2  785.59    41.9  774.94    53.7  762.63    61.9  755.97
    90.1  742.64   111.2  729.08   115.3  725.37   122.9  715.55   135.9  704.68
   146.5  693.78   150.7  690.64   174.3  677.42  180.38671.8167   184.2  670.56
   190.8  670.34  198.81671.8148   207.2  673.88   217.1  674.08   230.3  678.12
   269.8  676.52   297.9  676.38   309.6  677.53   316.7  679.92   328.2  687.63
   336.5  690.97   398.3  708.28     415  714.28   436.1  719.52   450.4  724.55
#Mann= 3 ,-1,0
       0      .1       0  180.38    .045       0  198.81      .1       0
Bank Sta=180.38,198.81
XS Rating Curve= 0 ,0
Exp/Cntr(USF)=0,0
Exp/Cntr=0.3,0.1

Type RM Length L Ch R = 1 ,4247    ,344.7,347,348.6
XS GIS Cut Line= 4
1589527.43193222465439.7957050011589610.98983597465472.328776414
1589760.52129411465520.4750716611589919.28088607465612.821933757
#Sta/Elev= 30
       0  810.77     7.1  808.25    14.2  804.43    33.5  791.72    41.1   785.8
    70.5  753.84    76.5   748.9   104.9  727.77   112.3  718.99   136.1  694.41
     144  687.65   156.7  678.02   160.5  674.37   164.8  671.91   191.6  672.74
   200.5 670.605   208.8  669.57  221.17670.6038   232.6  671.96   240.4  674.55
   280.9  675.76   288.4  676.47   303.6   680.9     315  687.73   322.9  691.33
   345.4  697.92   360.9  700.52   390.9  703.33   409.9  709.04   430.4  713.69
#Mann= 3 ,-1,0
       0      .1       0   200.5    .045       0  221.17      .1       0
Bank Sta=200.5,221.17
XS Rating Curve= 0 ,0
Exp/Cntr(USF)=0,0
Exp/Cntr=0.3,0.1

Type RM Length L Ch R = 1 ,3900    ,297.8,300,302.3
XS GIS Cut Line= 6
1589388.74924026465719.4235177491589465.77500483465760.935573846
 1589531.7971825465796.517851755  1589619.826534465843.960342169
1589685.84871167465879.5422919991589762.87447625465921.054676175
#Sta/Elev= 30
       0  750.71      16  746.22    36.9     737    42.1  736.13    45.8  734.75
    56.3  724.89    60.8  721.59    90.2  708.78   102.3  702.25   116.8  693.29
   127.8  688.64   146.5  682.32   187.5  667.16  196.33662.5681   202.4  661.43
   209.8  661.52  218.33662.5664   224.7   663.5   232.2  666.27   235.9  667.02
     297  669.79   317.7  669.27   338.5  672.78   355.2  679.49   366.4  681.96
   388.1  688.56   393.8  692.24   407.6  706.67   412.3  710.39     425  716.29
#Mann= 3 ,-1,0
       0      .1       0  196.33    .045       0  218.33      .1       0
Bank Sta=196.33,218.33
XS Rating Curve= 0 ,0
Exp/Cntr(USF)=0,0
Exp/Cntr=0.3,0.1

Type RM Length L Ch R = 1 ,3600    ,289.6,289.8,294.3
XS GIS Cut Line= 6
1589282.83705051465898.659707844 1589332.1561776465981.522731096
1589380.92281234 466042.153187261589456.18053584466108.003449261
 1589512.6239925466157.391145751 1589578.4745826466215.010125011
#Sta/Elev= 30
       0  718.61      23  712.54      47  710.83    61.5  708.34      89  707.72
   104.5  704.77   118.9  699.75   134.6  691.38   149.2  684.99   159.8  679.05
   167.4  676.61   184.2  673.61     197  668.65  216.31 656.736   229.5  655.89
  235.62 656.738     240  658.64   251.8  660.08   267.9  664.59   286.2  664.28
   298.1  667.95     308  672.15   347.2  679.69   360.3  685.88   386.4  701.86
   396.3  712.27   406.3  719.88   412.6  728.87   416.3  733.01   436.7   744.6
#Mann= 3 ,-1,0
       0      .1       0  216.31    .045       0  235.62      .1       0
Bank Sta=216.31,235.62
XS Rating Curve= 0 ,0
Exp/Cntr(USF)=0,0
Exp/Cntr=0.3,0.1

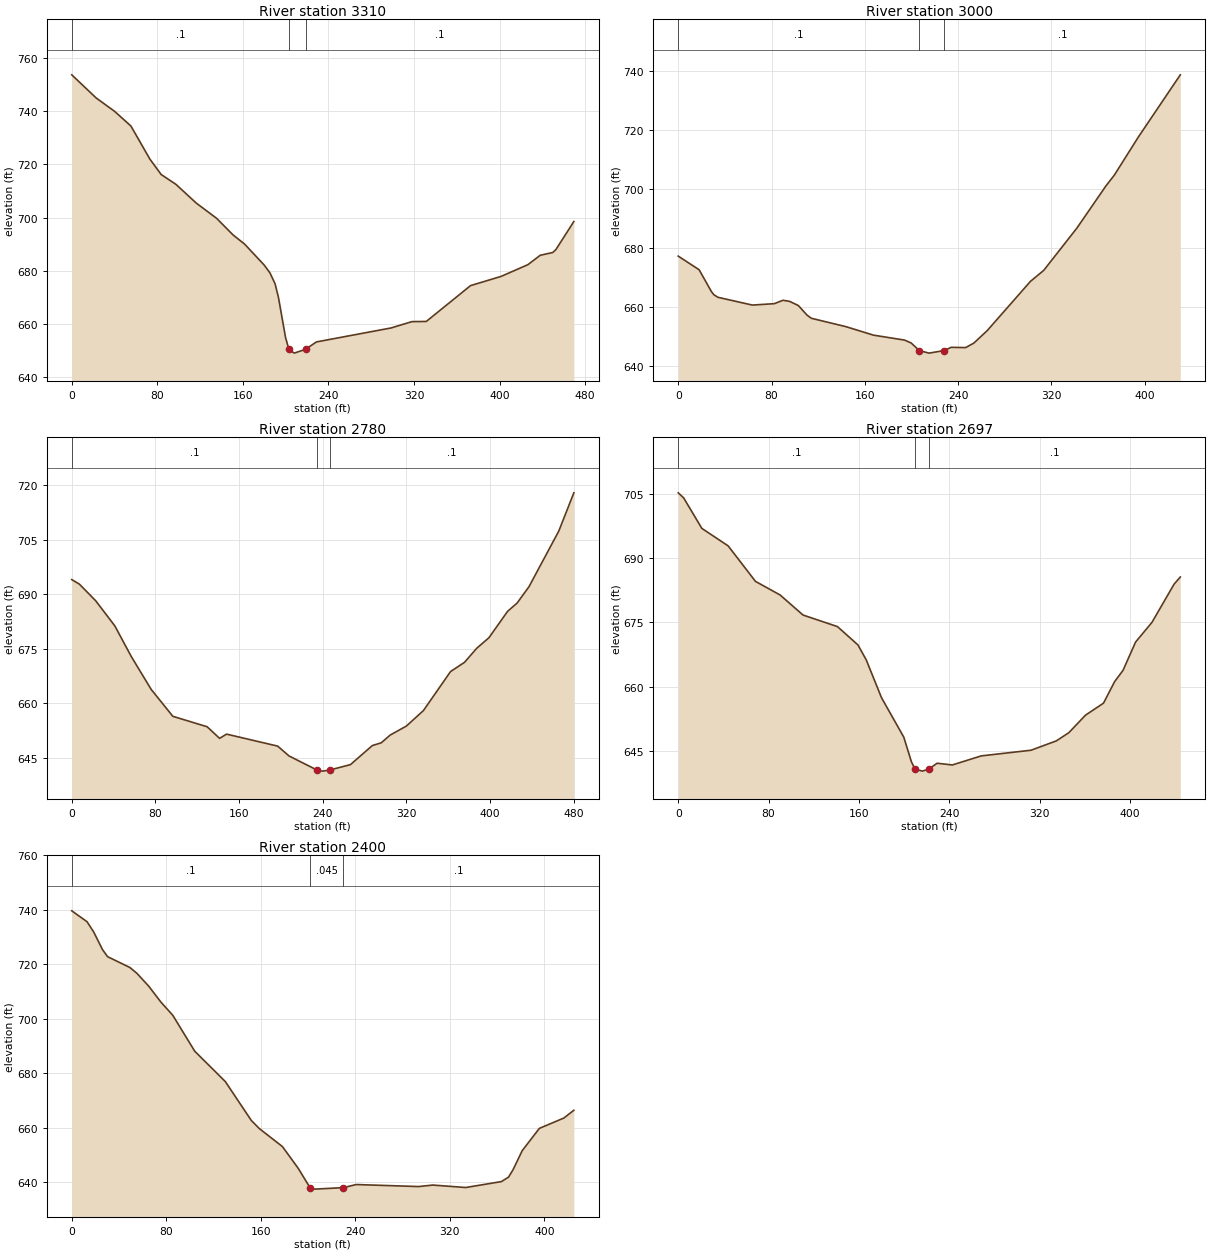
Type RM Length L Ch R = 1 ,3310    ,313,310.2,306.4
XS GIS Cut Line= 6
1589038.55998001 465970.297031761589083.31448367466045.482248843
1589121.77208392466109.871883839 1589190.7033765466185.454081759
1589257.31216717466257.0740172571589325.89044209466339.097803339
#Sta/Elev= 30
       0  753.66    22.8  744.97      40  739.95    55.3  734.43      73  722.02
    83.6  716.19    97.3  712.53   116.4  705.46   135.5  699.71   150.8  693.49
   161.6  690.05     180  682.14   185.3  679.24   190.1  675.15   193.3  669.96
   199.9  654.97     203650.5067     208  649.06  218.65650.5018   228.8  653.27
   298.6  658.52   318.1   660.9   331.5  660.96   372.9  674.43   401.4  677.89
   426.5   682.3   438.1  685.84   449.8  686.88   452.7  687.97   469.5  698.52
#Mann= 3 ,-1,0
       0      .1       0     203    .045       0  218.65      .1       0
Bank Sta=203,218.65
XS Rating Curve= 0 ,0
Exp/Cntr(USF)=0,0
Exp/Cntr=0.3,0.1

Type RM Length L Ch R = 1 ,3000    ,205.1,220.2,226.5
XS GIS Cut Line= 6
1588872.94482568466296.0234144181588937.31805651466362.082665503
1589004.11057384466397.3834479151589098.16583192466431.347946927
1589167.64764833466459.7560265961589248.05956101466494.699198172
#Sta/Elev= 30
       0   677.2    17.9  672.59    28.4  665.22    30.6   664.1    34.1  663.24
    63.6  660.61    82.4  661.09    89.8  662.24    95.6  661.86     103  660.45
   110.4  657.23   114.1  656.14   143.8   653.3   167.4  650.42   194.1  648.75
   199.7  647.77  206.74645.2051     215  644.33  228.13 645.206     234   646.3
   246.4   646.2   253.4  647.71   264.8   651.9     302  668.64   313.4  672.38
   341.8  686.68   366.8  701.03   373.9  704.62   394.6   717.6   430.5  738.63
#Mann= 3 ,-1,0
       0      .1       0  206.74    .045       0  228.13      .1       0
Bank Sta=206.74,228.13
XS Rating Curve= 0 ,0
Exp/Cntr(USF)=0,0
Exp/Cntr=0.3,0.1

Type RM Length L Ch R = 1 ,2780    ,85.2,82.5,78.1
XS GIS Cut Line= 5
1588794.40209162466338.5139274181588923.20127458466484.957468056
1588911.01702959466571.8558582611588936.68800202466602.891265078
1589045.36661308 466716.47893398
#Sta/Elev= 30
       0  694.08     7.3  692.82    22.9  688.25    41.2  681.34    56.9  672.93
      76  663.85    96.7  656.46   129.5  653.59   141.4   650.4   148.1  651.56
     197  648.26   207.8  645.56   234.6641.6811   240.1  641.38   246.7  641.68
   266.6  643.17   287.5  648.41   296.1  649.18   304.6   651.3   320.1  653.78
   336.4  658.04   362.4  668.79   375.7  671.31   387.5  675.21   399.1  678.09
   416.9  685.34     426  687.61   437.4  692.13   465.9  707.43   480.3  717.95
#Mann= 3 ,-1,0
       0      .1       0   234.6    .045       0   246.7      .1       0
Bank Sta=234.6,246.7
XS Rating Curve= 0 ,0
Exp/Cntr(USF)=0,0
Exp/Cntr=0.3,0.1

Type RM Length L Ch R = 1 ,2697    ,297.4,297.3,296.4
XS GIS Cut Line= 5
1588737.82731375466347.2336138341588779.64284693 466424.09533675
1588815.48463875466489.9767666761588858.51375218466580.408344343
1588941.95286641466742.040716866
#Sta/Elev= 30
       0  705.23     4.8  704.05    20.9  696.94    44.2  692.85    68.4  684.57
    90.2   681.4   110.5  676.72     141  674.02   159.1  669.75   166.4  666.29
     180  657.42   199.7  648.23   206.4  642.52   209.6  640.78   216.2  640.31
   221.8 640.782   229.2  642.15   242.7  641.75   268.2  643.86   312.4  645.19
   334.7  647.36   345.8  649.27   360.5  653.35   376.5  656.17   386.4  661.21
   393.8  663.82   404.9  670.42   419.4  675.01     439  683.93   444.5  685.59
#Mann= 3 ,-1,0
       0      .1       0   209.6    .045       0   221.8      .1       0
Bank Sta=209.6,221.8
XS Rating Curve= 0 ,0
Exp/Cntr(USF)=0,0
Exp/Cntr=0.3,0.1

Type RM Length L Ch R = 1 ,2400    ,258.9,257.5,250.7
XS GIS Cut Line= 6
1588477.25007901466524.1791260841588524.70602085466597.692430511
1588565.38244867466660.7037874161588619.61790451466744.719039336
1588660.29433234466807.7300681771588707.74994609466881.243372589
#Sta/Elev= 30
       0  739.62    12.9  735.64    18.5   731.9      26  725.41    30.3  722.81
    49.2  718.83    55.2  716.67      65  712.06    75.4  706.17    85.5  701.31
   104.1  688.12     130  676.98     152  662.71   158.8  659.73   178.3  653.15
   191.7  645.16   201.7  638.05   205.6  637.53   229.7  638.07   240.8  639.21
   293.7  638.47   305.6  639.02   333.5  638.12   363.7   640.3   369.7  641.93
   373.5  644.61   381.3  651.64   395.8  659.81   416.5   663.6     425  666.46
#Mann= 3 ,-1,0
       0      .1       0   201.7    .045       0   229.7      .1       0
Bank Sta=201.7,229.7
XS Rating Curve= 0 ,0
Exp/Cntr(USF)=0,0
Exp/Cntr=0.3,0.1