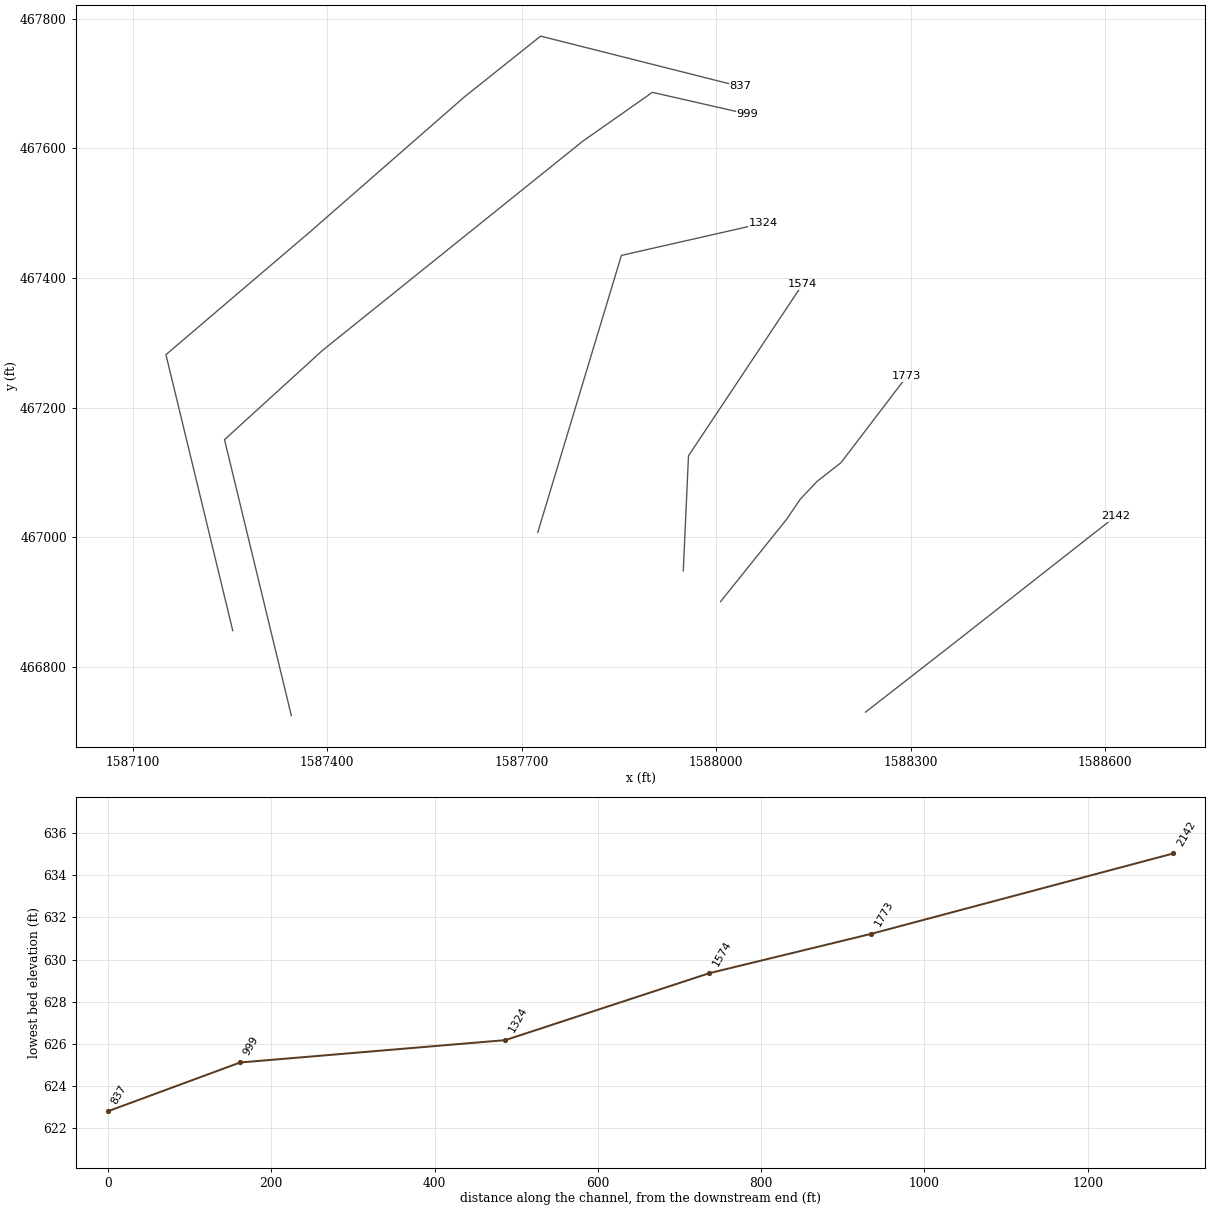
HEC-RAS study SimsRn.prj: SimsRn

--- SimsRn.g01 (geometry) --- (continued)

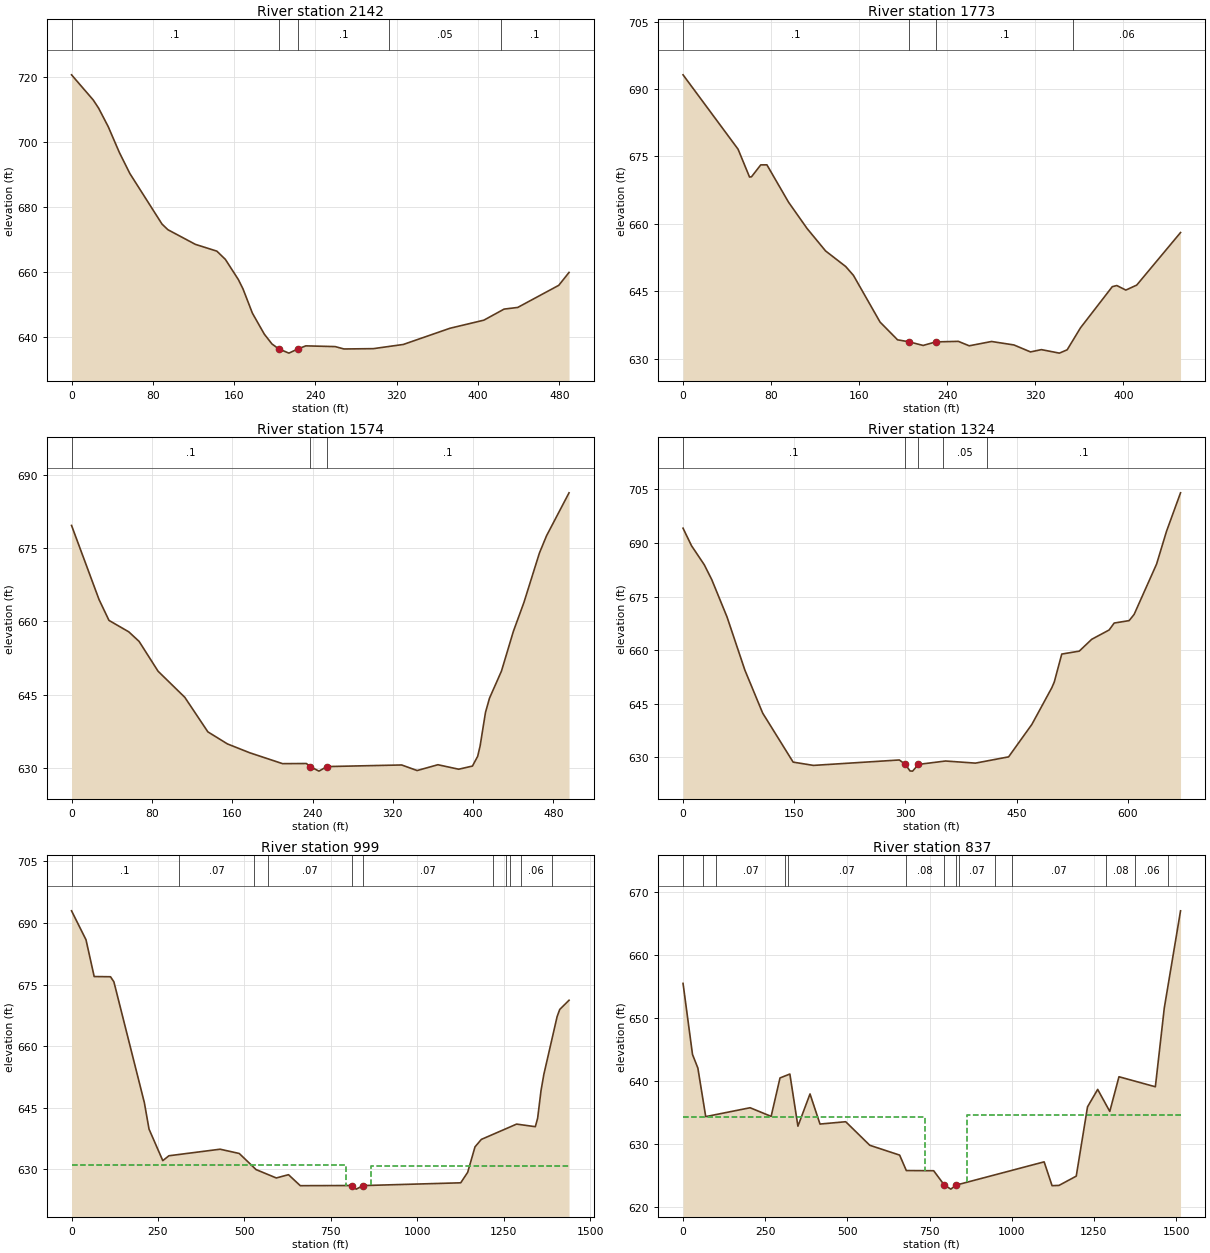
Type RM Length L Ch R = 1 ,2142    ,368.4,370,367.5
XS GIS Cut Line= 4
1588230.29465035466730.545834863 1588299.3348666 466784.30163286
1588358.51256976 466830.377984281588615.78983912467032.367853933
#Sta/Elev= 30
       0   720.8    21.4  713.03    26.6  710.55    36.1  704.83    47.1  696.84
    57.4  690.38      89  674.82    94.8  673.07   121.9  668.55     143  666.46
   151.4  663.92   164.2  657.69   168.7  654.86     178  647.34   189.7  640.89
   197.2  637.87  203.86636.3463   213.9  635.03   222.9636.3434   230.6  637.27
   259.5  637.04   268.1  636.31     297  636.41   326.5   637.7   372.4  642.69
   405.8  645.19   425.7   648.6   439.1  649.11   479.5  655.93   489.6   659.9
#Mann= 5 ,-1,0
       0      .1       0  203.86    .045       0   222.9      .1       0
   312.5     .05       0   422.5      .1       0
Bank Sta=203.86,222.9
XS Rating Curve= 0 ,0
Exp/Cntr(USF)=0,0
Exp/Cntr=0.3,0.1

Type RM Length L Ch R = 1 ,1773    ,194,198.8,196.4
XS GIS Cut Line= 6
1588006.78183168466901.0359792561588108.47126085467027.785725758
  1588129.905895467059.2195342891588155.61515182467086.357083164
1588192.38501787467115.1406621391588293.89658372467248.210772341
#Sta/Elev= 30
       0  693.15      50   676.6    60.4  670.41    62.2  670.46    70.6  673.11
    76.2  673.12    95.8  664.83   112.7  658.95   129.5  653.96   147.8  650.49
   154.8  648.53     179  638.13   194.9  634.18   205.3  633.74   218.1  632.93
   229.7  633.72   250.1  633.84     260  632.85   280.3  633.81   300.6  633.04
   315.7  631.49   325.6     632   341.9  631.22     349  631.96   361.1  636.85
     390  646.01   394.1  646.26   402.3  645.25   412.2  646.36     452  658.05
#Mann= 4 ,-1,0
       0      .1       0   205.3    .045       0   229.7      .1       0
  354.62     .06       0
Bank Sta=205.3,229.7
XS Rating Curve= 0 ,0
Exp/Cntr(USF)=0,0
Exp/Cntr=0.3,0.1

Type RM Length L Ch R = 1 ,1574    ,246.2,249.6,250.5
XS GIS Cut Line= 3
1587949.21204477466948.3868832281587957.27479518467125.767392141
1588133.31151235467390.494363776
#Sta/Elev= 30
       0  679.67    27.4  664.49    37.3  660.22      57  657.88    67.3  655.92
    86.2  649.81   112.8  644.47   135.8  637.39   155.3  634.92   177.6   633.1
   210.2  630.88   233.9  630.91   237.8630.2725   246.4  629.35  254.41630.2815
   328.8  630.61   344.2  629.47   364.9  630.66   385.6  629.74   399.3  630.39
   404.5  632.38   406.9  634.47   412.3  641.39   416.3   644.3   428.2  649.84
     440  657.94   450.6  663.91     466  674.02   473.1  677.56   495.5  686.35
#Mann= 3 ,-1,0
       0      .1       0   237.8    .045       0  254.41      .1       0
Bank Sta=237.8,254.41
XS Rating Curve= 0 ,0
Exp/Cntr(USF)=0,0
Exp/Cntr=0.3,0.1

Type RM Length L Ch R = 1 ,1324    ,327.7,324.9,305.3
XS GIS Cut Line= 3
1587724.79882516467007.5137195321587853.80283164467434.839491004
1588072.84088432467484.559785169
#Sta/Elev= 30
       0  694.14    11.4  689.25    28.6  683.93    38.8  679.73    59.4  669.27
    83.4  654.44   107.4  642.42   148.5   628.7   175.9  627.78   291.7   629.3
  299.92628.0675   306.1  626.23   309.6  626.18  317.49628.0598   354.1  629.01
   394.4  628.42   439.1  630.17   470.5  639.26   497.4  649.52   500.7  651.11
   510.8  658.93   534.4  659.75   551.2  663.06   574.7  665.67   581.5  667.61
   601.7  668.29   608.4  670.03   638.7  684.11   652.1  693.29     671  704.04
#Mann= 5 ,-1,0
       0      .1       0  299.92    .045       0  317.49      .1       0
     350     .05       0     410      .1       0
Bank Sta=299.92,317.49
XS Rating Curve= 0 ,0
Exp/Cntr(USF)=0,0
Exp/Cntr=0.3,0.1

Type RM Length L Ch R = 1 ,999     ,161.1,161.8,162.9
XS GIS Cut Line= 6
1587344.80438477 466725.168145161587241.78035182 467150.70219432
1587392.88226682467288.3661919781587794.37737496467611.025518375
1587901.58209331 467686.277855491588047.90608214 467652.98168252
#Sta/Elev= 30
       0  692.96    41.8  685.91    65.5  676.94   112.7  676.89   122.5  675.65
   210.6   646.2   224.1  639.75   263.9  632.06   281.5  633.25   429.6  634.85
     485  633.81   533.7  629.88   592.2  627.84   627.4  628.64   661.5  625.96
   810.8     626   823.2  625.12   843.4625.9839  1125.5  626.66  1145.6  629.22
  1166.8  635.43  1185.1  637.24  1287.1  640.97  1341.2  640.34  1347.9   642.4
  1357.6  649.09  1365.8  653.06  1404.2  667.17  1411.8  668.92  1438.7  671.16
#Mann= 11 ,-1,0
       0      .1       0     310     .07       0  527.83      .1       0
  567.83     .07       0   810.8    .045       0   843.4     .07       0
  1217.7     .08       0  1257.7     .06       0  1267.7     .08       0
 1298.68     .06       0 1388.68      .1       0
#XS Ineff= 2 , 0
          794.72  630.88  865.81          630.72
Permanent Ineff=
       F       F
Bank Sta=810.8,843.4
XS Rating Curve= 0 ,0
Exp/Cntr(USF)=0,0
Exp/Cntr=0.3,0.1

Type RM Length L Ch R = 1 ,837     ,,,
XS GIS Cut Line= 6
1587254.46574579466856.2326323011587151.44171284467281.766681461
1587373.91389994467471.3906261741587611.31710631467678.931794009
1587729.27215854467772.9972154031588036.85115547467695.355915205
#Sta/Elev= 30
       0  655.47    28.8  644.18    45.1  642.03      69  634.32     204  635.73
     268  634.36     295  640.46     325  641.08   349.5   632.8   386.3  637.92
   416.7  633.14   494.9  633.51   568.2  629.77     659  628.21   679.3  625.76
   762.5  625.73   794.7  623.47   814.7  622.81   831.1623.4529  1098.6  627.14
  1122.7  623.36  1143.8   623.4  1196.3  624.87  1230.6  635.87  1261.5  638.64
  1298.3  635.15  1326.3  640.65    1437  639.06  1464.1  651.54  1513.6  666.99
#Mann= 14 ,-1,0
       0      .1       0      60     .08       0     100     .07       0
     310     .08       0     320     .07       0  677.83     .08       0
   794.7    .045       0   831.1    .025       0  840.15     .07       0
  950.15    .025       0 1000.15     .07       0 1286.35     .08       0
 1376.35     .06       0 1476.35      .1       0
#XS Ineff= 2 , 0
          736.24  634.21  863.76          634.59
Permanent Ineff=
       F       F
Bank Sta=794.7,831.1
XS Rating Curve= 0 ,0
Exp/Cntr(USF)=0,0
Exp/Cntr=0.3,0.1
LCMann Table=0

Chan Stop Cuts=-1
Use User Specified Reach Order=0
Composite Channel Slope=5